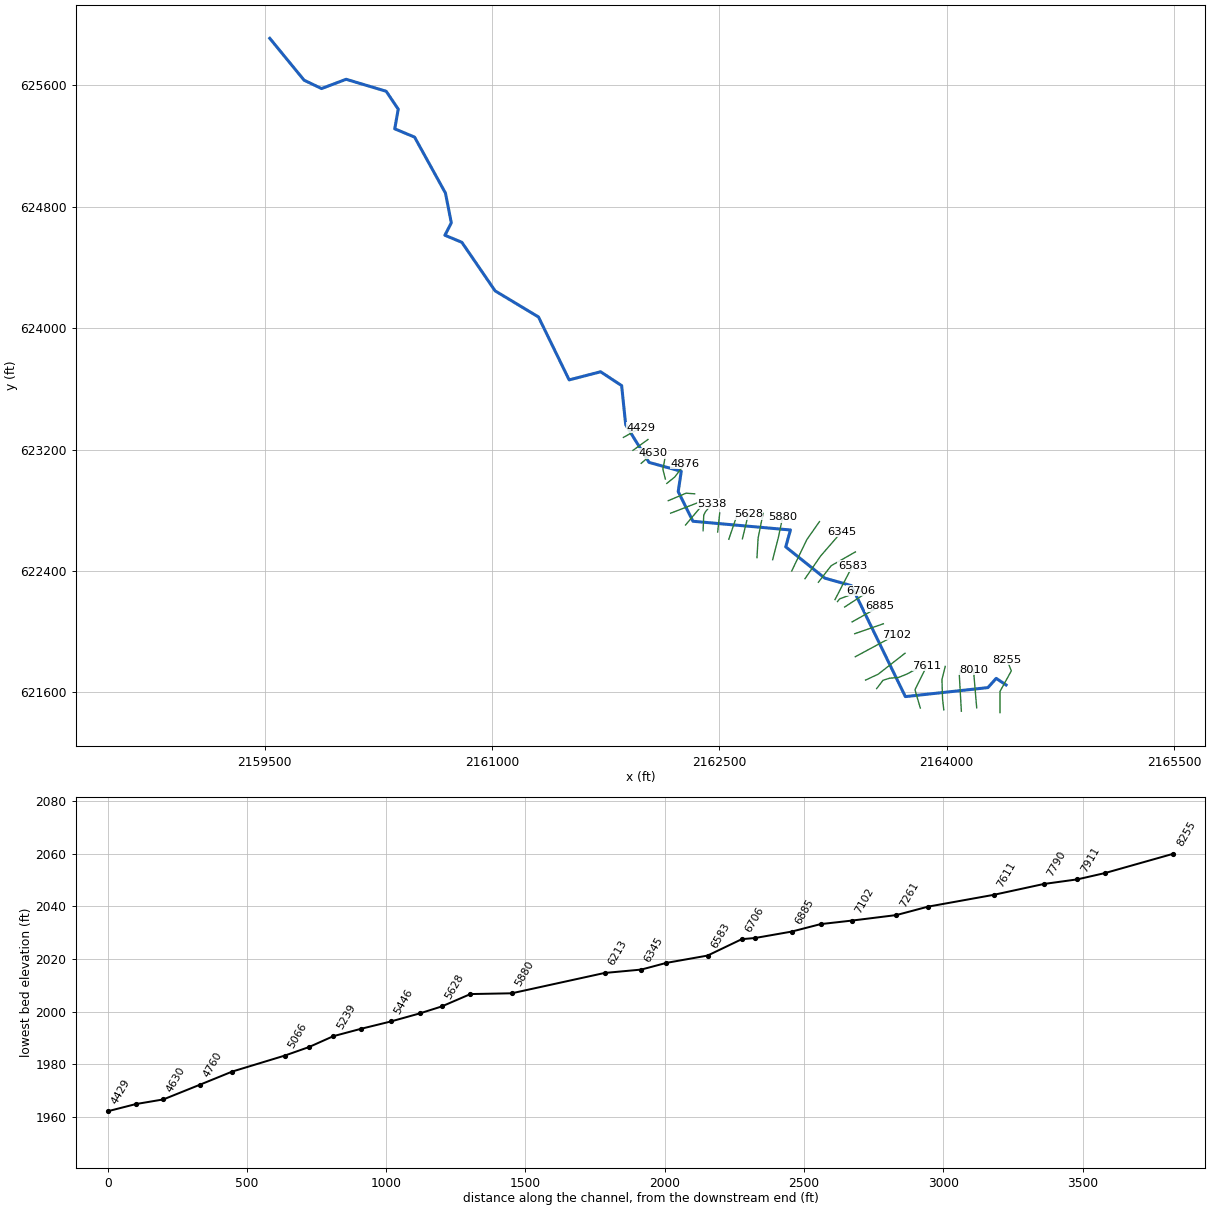
--- HOWELLFK.prj (project) ---

Proj Title=HOWELLFK
Current Plan=p01
Default Exp/Contr=0,0
English Units
Geom File=g01
Flow File=f01
Plan File=p01
BEGIN DESCRIPTION:
---------- MODELED AS PART OF WVEMD CTP PROGRAM, 2023----------
Stream Name: Howell Fork
Flood Zone:  AFH
Upshur County, WV
HEC-RAS Version: RAS 6.3
Vertical Datum: NAVD88
Projection: NAD 1983 StatePlane West Virginia S FIPS 4702 (US Feet)
Terrain: 1-meter LIDAR (FEMA Region III 3DEP collected 2016-2018)
Land Use: 2019 NLCD
Hydrologic Method:
WV SIR2010-5033 regression equations
Additional Model Notes:
None
END DESCRIPTION:
DSS Export Rating Curves= 0
DSS Export Rating Curve Sorted= 0
DSS Export Volume Flow Curves= 0
DXF OffsetX= 0
DXF OffsetY= 0
DXF ScaleX= 0
DXF ScaleY= 0

--- HOWELLFK.p01 (plan) ---

Plan Title=Floodplain
Program Version=6.30
Short Identifier=Floodplain
Geom File=g01
Flow File=f01
Subcritical Flow
K Sum by GR= 0
Std Step Tol= 0.01
Critical Tol= 0.01
Num of Std Step Trials= 20
Max Error Tol= 0.3
Flow Tol Ratio= 0.001
Split Flow NTrial= 30
Split Flow Tol= 0.02
Split Flow Ratio= 0.02
Log Output Level= 0
Friction Slope Method= 1
Unsteady Friction Slope Method= 2
Unsteady Bridges Friction Slope Method= 1
Parabolic Critical Depth
Global Vel Dist= 0 , 0 , 0
Global Log Level= 0
CheckData=False
Encroach Param=-1 ,0,0, 0
Mapping Interval=1HOUR
Computation Time Step Use Courant=        0
Computation Time Step Use Time Series=    0
Computation Time Step Count To Double=0
Computation Time Step Max Doubling=0
Computation Time Step Max Halving=0
Computation Time Step Residence Courant=0
Run HTab= 0
Run UNet= 0
Run Sediment= 0
Run PostProcess= 0
Run WQNet= 0
Run RASMapper=-1
UNET Theta= 0
UNET Theta Warmup= 0
UNET ZTol= 0
UNET ZSATol= 0
UNET MxIter= 0
UNET Max Iter WO Improvement= 0
UNET MaxInSteps= 0
UNET DtIC= 0
UNET DtMin= 0
UNET MaxCRTS= 0
UNET WFStab= 0
UNET SFStab= 0
UNET WFX= 1
UNET SFX= 1
UNET Gravity=32.17405
UNET 1D Methodology=Finite Difference
UNET DSS MLevel= 1
UNET Pardiso=0
UNET DZMax Abort= 0
UNET Use Existing IB Tables= 0
UNET Froude Reduction=False
UNET Froude Limit= 0
UNET Froude Power= 0
UNET D1 Cores= 0
UNET WindReference=Eulerian
UNET WindDragFormulation=Hsu (1988)
UNET D2 Coriolis=0
UNET D2 Cores= 0
UNET D2 Theta= 1
UNET D2 Theta Warmup= 1
UNET D2 Z Tol= 0.01
UNET D2 Volume Tol= 0.01
UNET D2 Max Iterations= 20
UNET D2 Equation= 0
UNET D2 RampUpFraction=0.1
UNET D2 TimeSlices= 1
UNET D2 Turbulence Formulation=Non-Conservative (original)
UNET D2 Eddy Viscosity=0.3
UNET D2 Transverse Eddy Viscosity=0.1
UNET D2 Smagorinsky Mixing=0
UNET D2 BCVolumeCheck=0
UNET D2 Cores=0
UNET D2 SolverType=PARDISO (Direct)
UNET D2 Minimum Iterations= 3
UNET D2 Maximum Iterations= 30
UNET D2 Restart Number= 10
UNET D2 Relaxation Coeff=1.3
UNET D2 SOR Precondition Iterations= 10
UNET D2 ILUT Maximum Fill= 8
UNET D2 ILUT Tolerance=1E-08
UNET D2 Convergence Tolerance=0.00001
UNET D1D2 MaxIter= 0
UNET D1D2 ZTol=0.01
UNET D1D2 QTol=0.1
UNET D1D2 MinQTol=1
Write IC File= 0
Write IC File at Fixed DateTime=0
Write IC File at Sim End=0
Echo Input=False
Echo Parameters=False
Echo Output=False
Write Detailed= 0
HDF Write Warmup=0
HDF Write Time Slices=0
HDF Flush=0
HDF Compression= 1
HDF Chunk Size= 1
HDF Spatial Parts= 1
HDF Use Max Rows=0
HDF Fixed Rows= 1
Calibration Method= 0
Calibration Iterations= 20
Calibration Max Change=0.05
Calibration Tolerance=0.2
Calibration Maximum=1.5
Calibration Minimum=0.5
Calibration Optimization Method= 1
WQ AD Non Conservative
WQ ULTIMATE=-1
WQ Max Comp Step=1HOUR
WQ Output Interval=15MIN
WQ Output Selected Increments= 0
WQ Output face flow=0
WQ Output face velocity=0
WQ Output face area=0
WQ Output face dispersion=0
WQ Output cell volume=0
WQ Output cell surface area=0
WQ Output cell continuity=0
WQ Output cumulative cell continuity=0
WQ Output face conc=0
WQ Output face dconc_dx=0
WQ Output face courant=0
WQ Output face peclet=0
WQ Output face adv mass=0
WQ Output face disp mass=0
WQ Output cell mass=0
WQ Output cell source sink temp=0
WQ Output nsm pathways=0
WQ Output nsm derived pathways=0
WQ Create Restart=0
WQ Fixed Restart=0
WQ System Summary=0
WQ Write To DSS=0
Sorting and Armoring Iterations= 10
XS Update Threshold= 0.02
Bed Roughness Predictor= 0
Hydraulics Update Threshold= 0.02
Energy Slope Method= 1
Volume Change Method= 1
Sediment Retention Method= 0
Sediment TS Multiplier= 1
Warm Up Method= 0
XS Weighting Method= 0
Number of US Weighted Cross Sections= 1
Number of DS Weighted Cross Sections= 1
Upstream XS Weight=0
Main XS Weight=1
Downstream XS Weight=0
Number of DS XS's Weighted with US Boundary= 1
Upstream Boundary Weight= 1
Weight of XSs Associated with US Boundary= 0
Number of US XS's Weighted with DS Boundary= 1
Downstream Boundary Weight= 0.5
Weight of XSs Associated with DS Boundary= 0.5
Percentile Method= 0
Sediment Output Level= 3
Mass or Volume Output= 0
Output Increment Type= 1
Profile and TS Output Increment= 1
Transport Output Increment 1
XS Output Flag= 0
XS Output Increment= 10
Read HDF5 Sediment Hotstart= 0
Sediment Hotstart Type= 0
Write Gradation File= 0
Read Gradation Hotstart= 0
Write HDF5 File= 1
Write Binary Output= 1
Write DSS Sediment File= 0
DSS Sediment Output Type= 1
SV Curve= 0
Specific Gage Flag= 0
Subcell Erosion Methods= 0
Subcell Deposition Methods= 0
Advection Scheme= 1
Matrix Solver= 0
Implicit Weighting Factor= 1
Maximum Outer Loop Convergence Iterations= 5
Convergence Maximum Absolute= 0.001
Convergence RMSE= 0.0001
Grain Fractions Max Abs Error= 0.001
Max Subgrid Regions= 1
Max Subgrid Length Scale= 3.402823E+38
Initial Layer Thickness= 3.402823E+38
Min Layer Thickness= 3.402823E+38
Max Layer Thickness= 3.402823E+38
Number of Layers= 5

--- HOWELLFK.f01 (steady flow) ---

Flow Title=Flows
Program Version=6.31
Number of Profiles= 1
Profile Names=01pct
River Rch & RM=HOWELLFK,Main,8255
     837
Boundary for River Rch & Prof#=HOWELLFK,Main            , 1
Up Type= 0
Dn Type= 3
Dn Slope=0.05386
DSS Import GetInterval= 0
DSS Import GetPeak= 0
DSS Import FillOption= 0

--- HOWELLFK.g01 (geometry) ---

Geom Title=Geometry
Program Version=6.31

River Reach=HOWELLFK        ,Main
Reach XY= 30
2164391.95814379621648.2027852982164326.59466711621691.607325718
     2164272.204621630.7539999932163727.43400003621571.403000012
2163371.21700004622303.0960000162163196.28500003622352.115999997
2162938.22200002622558.439999998       2162969.5622669.643000022
     2162326.146 622727.076000022162229.10800001622922.383000016
     2162249.111623056.451000005      2162036.72623115.056999996
     2161882.535623363.4190000152161855.83600001623621.167000011
     2161717.075623712.4819999932161509.54900004623658.854000002
2161307.20299999 624073.82100001     2161021.382624245.518999994
2160801.69400004      624565.794     2160689.976624612.267000005
2160732.32800002 624693.995000022160693.57765913 624890.35807614
2160489.93042028625259.1159564412160359.05600001625313.711999998
2160382.20700002 625443.115000012160302.59600002625561.272000015
2160038.23800005625640.3100000022159876.32600003 625579.15700002
2159761.17399998625634.1580000222159534.58812457625910.395264574

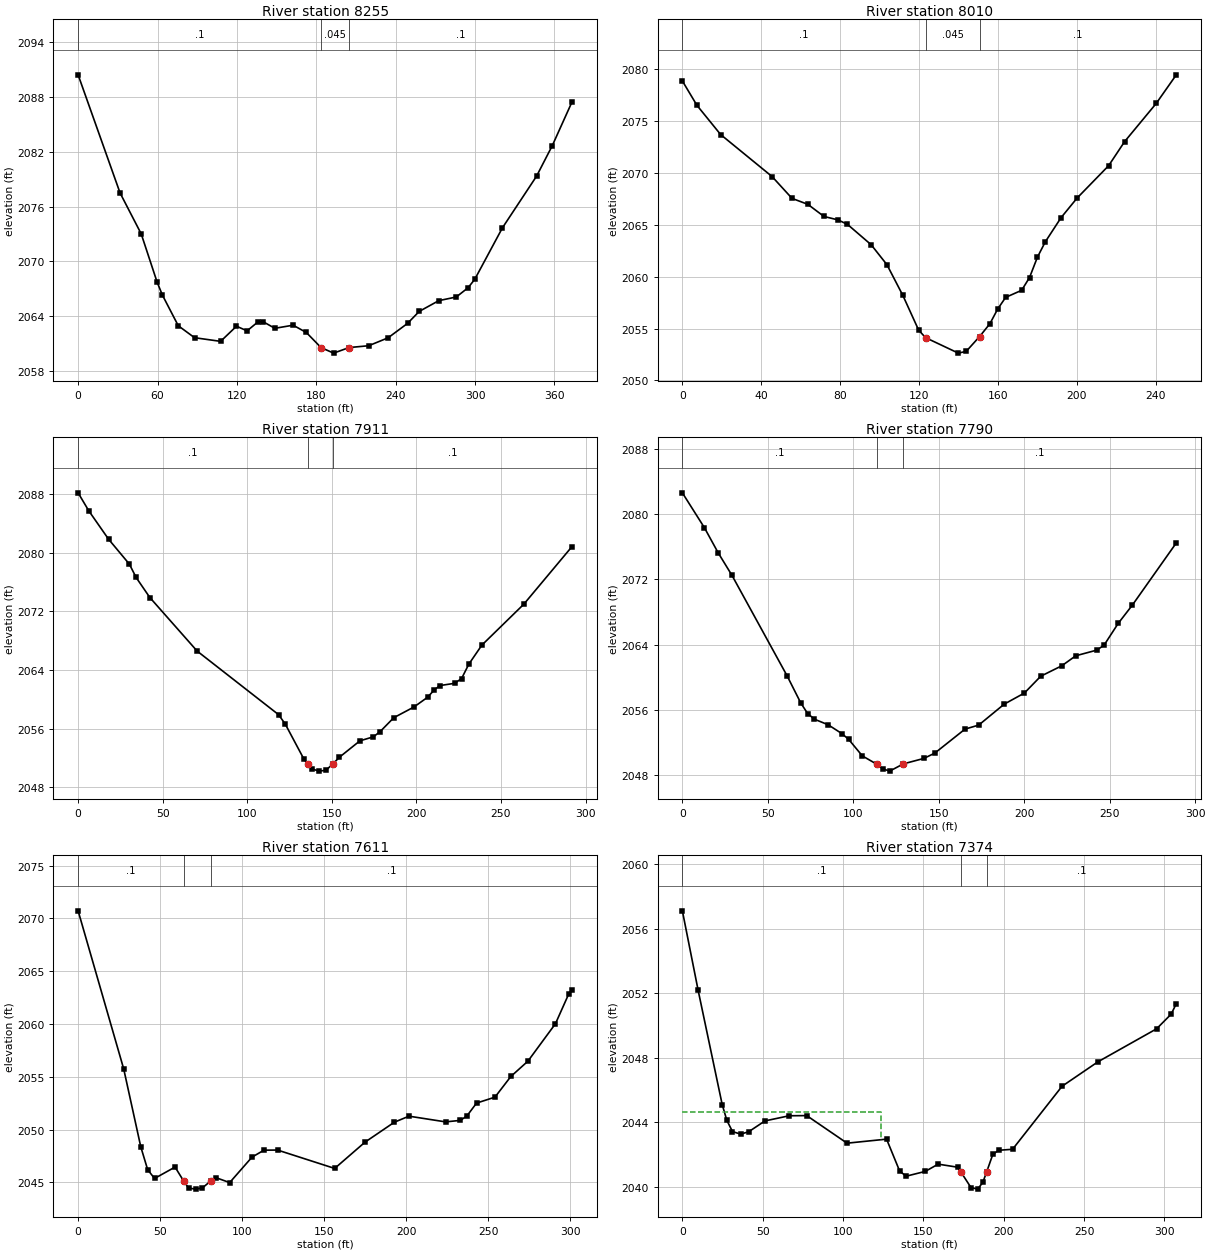
Type RM Length L Ch R = 1 ,8255    ,245.1,245.1,245.1
XS GIS Cut Line= 4
2164351.69990967621465.4583813632164351.96368949621605.956299446
2164426.50982418621740.9872914942164397.67828004621814.042732767
#Sta/Elev= 30
       0 2090.45    31.7 2077.51    47.7 2073.02    59.7 2067.74    63.7 2066.32
    75.7 2062.96      88 2061.65   107.7 2061.25   119.7 2062.91   127.7  2062.4
   135.9 2063.38   139.7 2063.41   148.7 2062.68   162.5 2063.02   172.5 2062.22
  183.58 2060.57   193.1 2059.96   204.8 2060.57   219.6 2060.77   234.3 2061.64
     249 2063.22   257.8 2064.53   272.6 2065.71   285.8 2066.11   294.7 2067.12
   299.8 2068.05   320.7 2073.69   346.5 2079.35   358.4  2082.7   373.3 2087.49
#Mann= 3 ,-1,0
       0      .1       0  183.58    .045       0   204.8      .1       0
Bank Sta=183.58,204.8
XS Rating Curve= 0 ,0
Exp/Cntr(USF)=0,0
Exp/Cntr=0.3,0.1

Type RM Length L Ch R = 1 ,8010    ,99.3,99.7,99.7
XS GIS Cut Line= 2
2164198.05233617621497.814727968 2164176.9325137621747.298509232
#Sta/Elev= 30
       0 2078.84     7.4 2076.49    19.4 2073.68    45.5 2069.63    55.6 2067.53
    63.6 2066.96    71.8 2065.79    78.9 2065.46    83.7 2065.03    95.7 2063.07
   103.7 2061.15   111.8 2058.18   119.8 2054.84   123.3 2054.12   139.9 2052.63
   143.9  2052.8   150.7 2054.23   155.9 2055.46   159.9 2056.89   163.9    2058
     172 2058.68     176 2059.91     180 2061.87     184 2063.35     192 2065.68
   200.1 2067.56   216.1 2070.68   224.2    2073   240.2 2076.67   250.4 2079.43
#Mann= 3 ,-1,0
       0      .1       0   123.3    .045       0   150.7      .1       0
Bank Sta=123.3,150.7
XS Rating Curve= 0 ,0
Exp/Cntr(USF)=0,0
Exp/Cntr=0.3,0.1

Type RM Length L Ch R = 1 ,7911    ,120.6,120.8,119.4
XS GIS Cut Line= 3
2164096.92725485621474.8930428682164083.44391067 621712.19990037
2164096.92725485621764.784942657
#Sta/Elev= 30
       0 2088.16     6.3 2085.71      18 2081.84    30.3 2078.44    34.3 2076.62
    42.4 2073.89    70.4 2066.58   118.5 2057.92   122.5 2056.62   133.3 2051.94
   135.82051.148   138.5  2050.5   142.5 2050.22   146.5 2050.34   150.52051.175
   154.5 2052.12   166.6 2054.35   174.6  2054.9   178.6 2055.62   186.6  2057.5
   198.6 2058.97   206.6 2060.29   210.6 2061.31     214 2061.89   222.6 2062.19
   226.7 2062.84     231 2064.81   238.7  2067.4   263.5 2072.98     292 2080.84
#Mann= 3 ,-1,0
       0      .1       0   135.8    .045       0   150.5      .1       0
Bank Sta=135.8,150.5
XS Rating Curve= 0 ,0
Exp/Cntr(USF)=0,0
Exp/Cntr=0.3,0.1

Type RM Length L Ch R = 1 ,7790    ,173.9,178.7,180.8
XS GIS Cut Line= 4
2163980.97049493621484.3313837922163972.88048843621555.793107926
2163968.83548517  621683.88487762163990.40883585621770.178280328
#Sta/Elev= 30
       0 2082.62    12.9 2078.34      21 2075.24      29  2072.5    61.2 2060.19
    69.3 2056.82    73.3 2055.53    77.3 2054.83    85.3 2054.15    93.3 2053.07
    97.3 2052.36   105.3 2050.33   113.9 2049.29   117.3 2048.74   121.3 2048.46
   129.3 2049.35   141.3 2050.02   147.7 2050.67   165.4 2053.62   173.4 2054.11
   188.3 2056.68   200.1 2058.04   209.7 2060.11     222 2061.39   230.2 2062.62
   242.6 2063.32   246.8 2063.94     255 2066.59   263.3 2068.84     289 2076.47
#Mann= 3 ,-1,0
       0      .1       0   113.9    .045       0   129.3      .1       0
Bank Sta=113.9,129.3
XS Rating Curve= 0 ,0
Exp/Cntr(USF)=0,0
Exp/Cntr=0.3,0.1

Type RM Length L Ch R = 1 ,7611    ,256.5,237.3,215.4
XS GIS Cut Line= 3
 2163825.9120369 621496.466393552163790.85534205621616.468156719
2163869.05873827 621774.22328358
#Sta/Elev= 30
       0 2070.72    27.8 2055.74    38.2 2048.37    42.4  2046.2    46.6 2045.37
    59.1 2046.45    64.42045.111    67.4 2044.46    71.6 2044.36    75.8 2044.48
    80.9 2045.14    84.1 2045.44    92.4 2044.98     106 2047.39   113.3 2048.05
   121.6 2048.06   156.4 2046.32   174.9 2048.81   192.8  2050.7   201.7 2051.27
     224 2050.73     233 2050.87     237 2051.29   242.9 2052.51   254.1 2053.07
   263.8 2055.03   274.2 2056.48     291 2060.03   299.1 2062.85   301.1 2063.21
#Mann= 3 ,-1,0
       0      .1       0    64.4    .045       0    80.9      .1       0
Bank Sta=64.4,80.9
XS Rating Curve= 0 ,0
Exp/Cntr(USF)=0,0
Exp/Cntr=0.3,0.1

Type RM Length L Ch R = 1 ,7374    ,102.7,112.8,117.5
XS GIS Cut Line= 6
2163538.21914304621624.3583827592163579.95176031621678.990419831
2163623.78447299621692.7382330122163683.94620506621698.034400011
2163738.12694982621720.212750411 2163802.9915638 621755.24339076
#Sta/Elev= 30
       0  2057.1     9.8 2052.18    24.8 2045.08    27.7  2044.1    31.2 2043.41
    36.3 2043.25    41.3  2043.4    51.4 2044.07    66.5 2044.39    77.4  2044.4
   102.5 2042.69   127.1 2042.94   135.2 2040.97   139.2 2040.64   151.2 2040.94
   159.2 2041.39   171.3  2041.2   173.32040.911   179.6 2039.94   183.8 2039.84
     187 2040.26  189.372040.906   193.2 2041.99   196.8 2042.25   205.5 2042.31
   236.3 2046.22   258.7 2047.74   295.1 2049.78   304.2 2050.69   307.4 2051.34
#Mann= 3 ,-1,0
       0      .1       0   173.3    .045       0  189.37      .1       0
#XS Ineff= 2 , 0
          123.44 2044.63
Permanent Ineff=
       F       F
Bank Sta=173.3,189.37
XS Rating Curve= 0 ,0
Exp/Cntr(USF)=0,0
Exp/Cntr=0.3,0.1

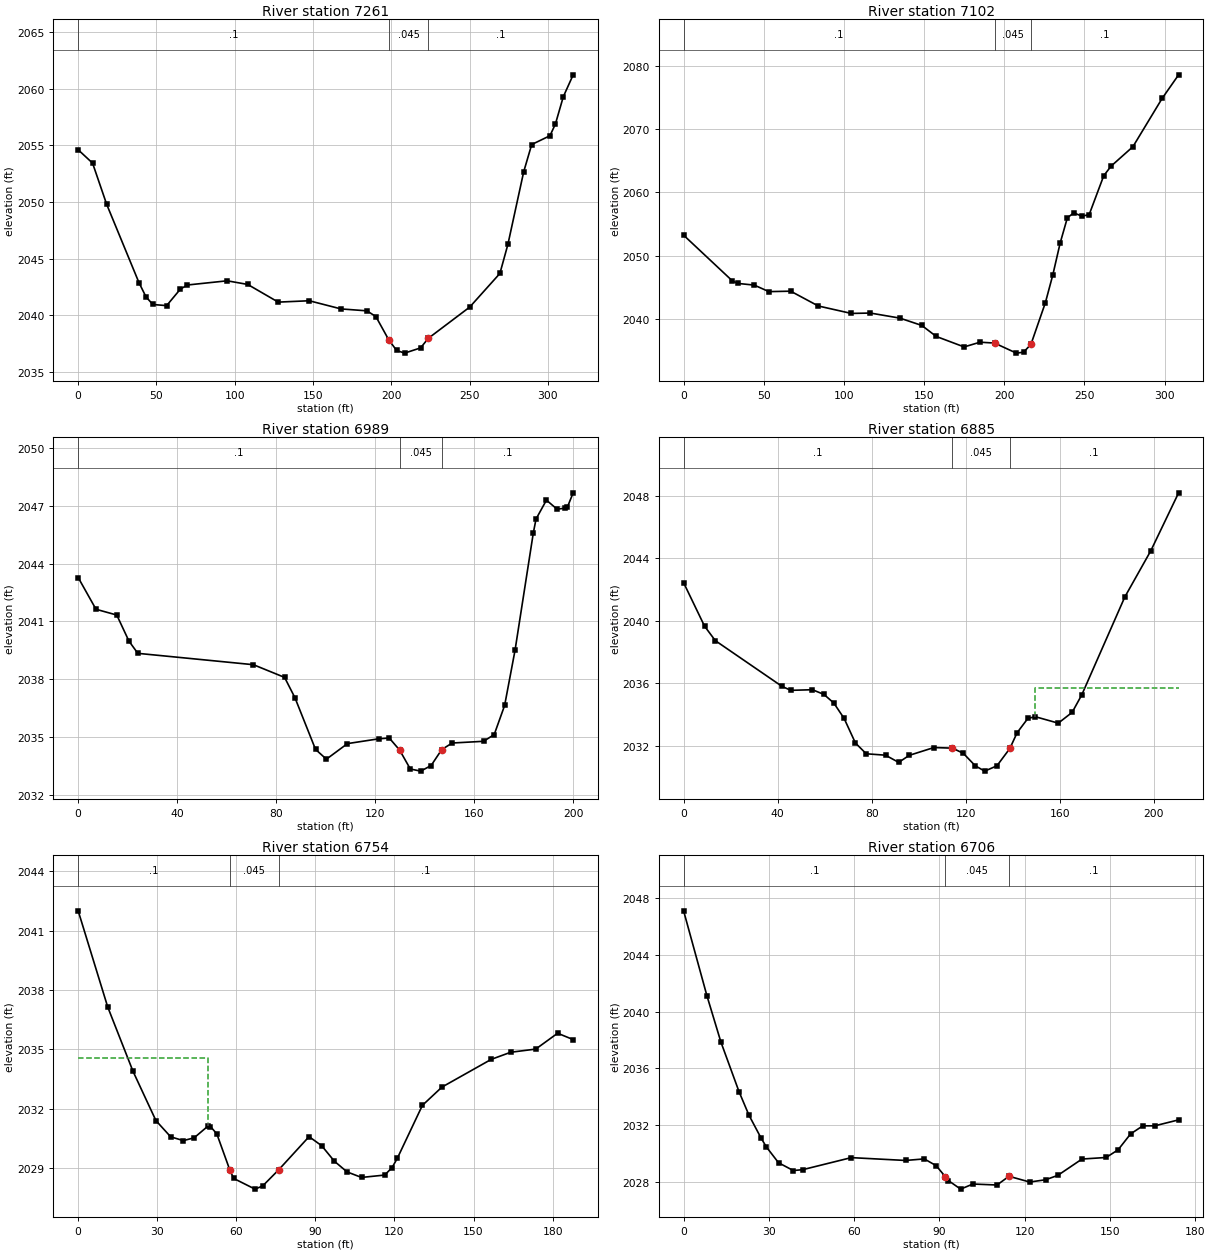
Type RM Length L Ch R = 1 ,7261    ,161.8,159.1,155
XS GIS Cut Line= 3
2163464.99950068 621680.143027542163548.15586855621719.067284841
2163725.08431083 621857.07146982
#Sta/Elev= 30
       0  2054.6     9.2 2053.42    18.2 2049.79    38.8 2042.89    43.3 2041.63
    47.7 2040.95    56.5 2040.85    65.3 2042.31    69.8 2042.67    95.2 2043.04
   108.3 2042.72   127.8 2041.16   147.6 2041.28   167.9 2040.56   184.5 2040.39
   190.2 2039.88   198.4 2037.83   203.4  2036.9   208.5 2036.66   218.7 2037.12
   223.7 2037.97   250.1 2040.72   269.4 2043.69   274.5 2046.25   284.6 2052.66
   289.7 2055.06   301.4 2055.84   304.9 2056.89   309.9 2059.28   316.2 2061.21
#Mann= 3 ,-1,0
       0      .1       0   198.4    .045       0   223.7      .1       0
Bank Sta=198.4,223.7
XS Rating Curve= 0 ,0
Exp/Cntr(USF)=0,0
Exp/Cntr=0.3,0.1

Type RM Length L Ch R = 1 ,7102    ,115.9,113.2,111.7
XS GIS Cut Line= 2
 2163397.3597572621834.2565471882163669.32327732621980.616547111
#Sta/Elev= 30
       0 2053.23    30.5 2045.98    33.8  2045.6    44.1 2045.33    53.2  2044.3
    66.8 2044.37      84 2042.03   104.6 2040.85   116.5 2040.91   134.9 2040.11
   148.6 2038.95   157.6 2037.21     175 2035.55   184.9  2036.3     194 2036.16
   207.6 2034.57   212.1 2034.72   216.7 2035.97   225.7 2042.56   230.3 2046.92
   234.9 2051.98   239.4 2055.98   243.4 2056.76   248.5 2056.24     253 2056.48
   262.1 2062.64   266.7 2064.16   280.3 2067.23   298.5 2074.86   308.8  2078.6
#Mann= 3 ,-1,0
       0      .1       0     194    .045       0   216.7      .1       0
Bank Sta=194,216.7
XS Rating Curve= 0 ,0
Exp/Cntr(USF)=0,0
Exp/Cntr=0.3,0.1

Type RM Length L Ch R = 1 ,6989    ,100.4,103.8,106.2
XS GIS Cut Line= 2
2163393.40076931621985.8960329862163582.34287125622051.425085683
#Sta/Elev= 30
       0 2043.28     7.2 2041.63    15.6 2041.33    20.5 2039.98    24.1 2039.34
    70.8 2038.75    83.4 2038.09    87.6 2037.03    95.9 2034.35   100.3 2033.84
   108.8 2034.65   121.5  2034.9   125.7 2034.94   129.9 2034.31   134.2 2033.33
   138.4 2033.22   142.6 2033.51   146.9 2034.34   151.1 2034.68   163.8 2034.77
   168.1 2035.12   172.3 2036.63   176.5 2039.49   183.9  2045.6     185 2046.32
   189.2  2047.3   193.5 2046.83   196.5 2046.88   197.7 2046.95     200 2047.68
#Mann= 3 ,-1,0
       0      .1       0   129.9    .045       0   146.9      .1       0
Bank Sta=129.9,146.9
XS Rating Curve= 0 ,0
Exp/Cntr(USF)=0,0
Exp/Cntr=0.3,0.1

Type RM Length L Ch R = 1 ,6885    ,127.2,131,132.1
XS GIS Cut Line= 2
2163376.39162732622064.0041083232163560.09372178622166.953974574
#Sta/Elev= 30
       0 2042.44     8.9 2039.66    13.5 2038.73    41.8 2035.81    45.6 2035.55
    54.8 2035.59    59.7 2035.29    63.9 2034.74    68.3 2033.75    73.1 2032.18
    77.7 2031.49    85.9  2031.4    91.5 2030.94      96 2031.39   106.5 2031.89
   114.4 2031.85     119 2031.52   124.1 2030.72   128.1 2030.38   133.3 2030.72
   138.8 2031.83   141.9 2032.84   146.5 2033.76   149.7 2033.86   159.4 2033.45
   165.3 2034.14   169.4 2035.26   187.7 2041.52   198.8 2044.49   210.6 2048.19
#Mann= 3 ,-1,0
       0      .1       0   114.4    .045       0   138.8      .1       0
#XS Ineff= 2 , 0
                           149.3         2035.68
Permanent Ineff=
       F       F
Bank Sta=114.4,138.8
XS Rating Curve= 0 ,0
Exp/Cntr(USF)=0,0
Exp/Cntr=0.3,0.1

Type RM Length L Ch R = 1 ,6754    ,51.2,48.2,47.9
XS GIS Cut Line= 2
2163326.77956573622161.732324389 2163484.0492922622264.394506947
#Sta/Elev= 30
       0    2042    11.2 2037.15    20.8  2033.9    29.5 2031.41    35.1 2030.59
    39.9  2030.4      44 2030.54    49.4 2031.15    50.2 2031.11    52.6 2030.74
    57.5 2028.93      59 2028.49    67.1 2027.95      70 2028.11    76.12028.929
    87.6  2030.6    92.4 2030.14    97.2 2029.36     102 2028.82   107.5 2028.54
   116.3 2028.66   119.1 2029.04   121.1 2029.51   130.6 2032.18     138  2033.1
   156.7  2034.5   164.1 2034.86   173.6 2035.02   181.9 2035.82   187.8  2035.5
#Mann= 3 ,-1,0
       0      .1       0    57.5    .045       0    76.1      .1       0
#XS Ineff= 2 , 0
           49.28 2034.55
Permanent Ineff=
       F       F
Bank Sta=57.5,76.1
XS Rating Curve= 0 ,0
Exp/Cntr(USF)=0,0
Exp/Cntr=0.3,0.1

Type RM Length L Ch R = 1 ,6706    ,111,122.7,128.2
XS GIS Cut Line= 3
2163279.83396609622197.9335625012163294.41457922622215.695563123
2163435.99465356 622268.76311046
#Sta/Elev= 30
       0 2047.11     8.2 2041.13    13.1 2037.88    19.5 2034.37      23 2032.71
    27.2 2031.12    29.1 2030.48    33.4 2029.36    38.6 2028.81    41.9 2028.87
      59 2029.72    78.1 2029.52    84.7 2029.63    88.9 2029.15    92.12028.375
    93.2  2028.1    97.5  2027.5   101.8 2027.86   110.3 2027.79   114.52028.406
   121.8    2028   127.4 2028.16   131.7 2028.47   140.2 2029.62   148.7 2029.73
   152.9 2030.27   157.3 2031.39   161.6 2031.96   165.8 2031.96   174.2 2032.38
#Mann= 3 ,-1,0
       0      .1       0    92.1    .045       0   114.5      .1       0
Bank Sta=92.1,114.5
XS Rating Curve= 0 ,0
Exp/Cntr(USF)=0,0
Exp/Cntr=0.3,0.1

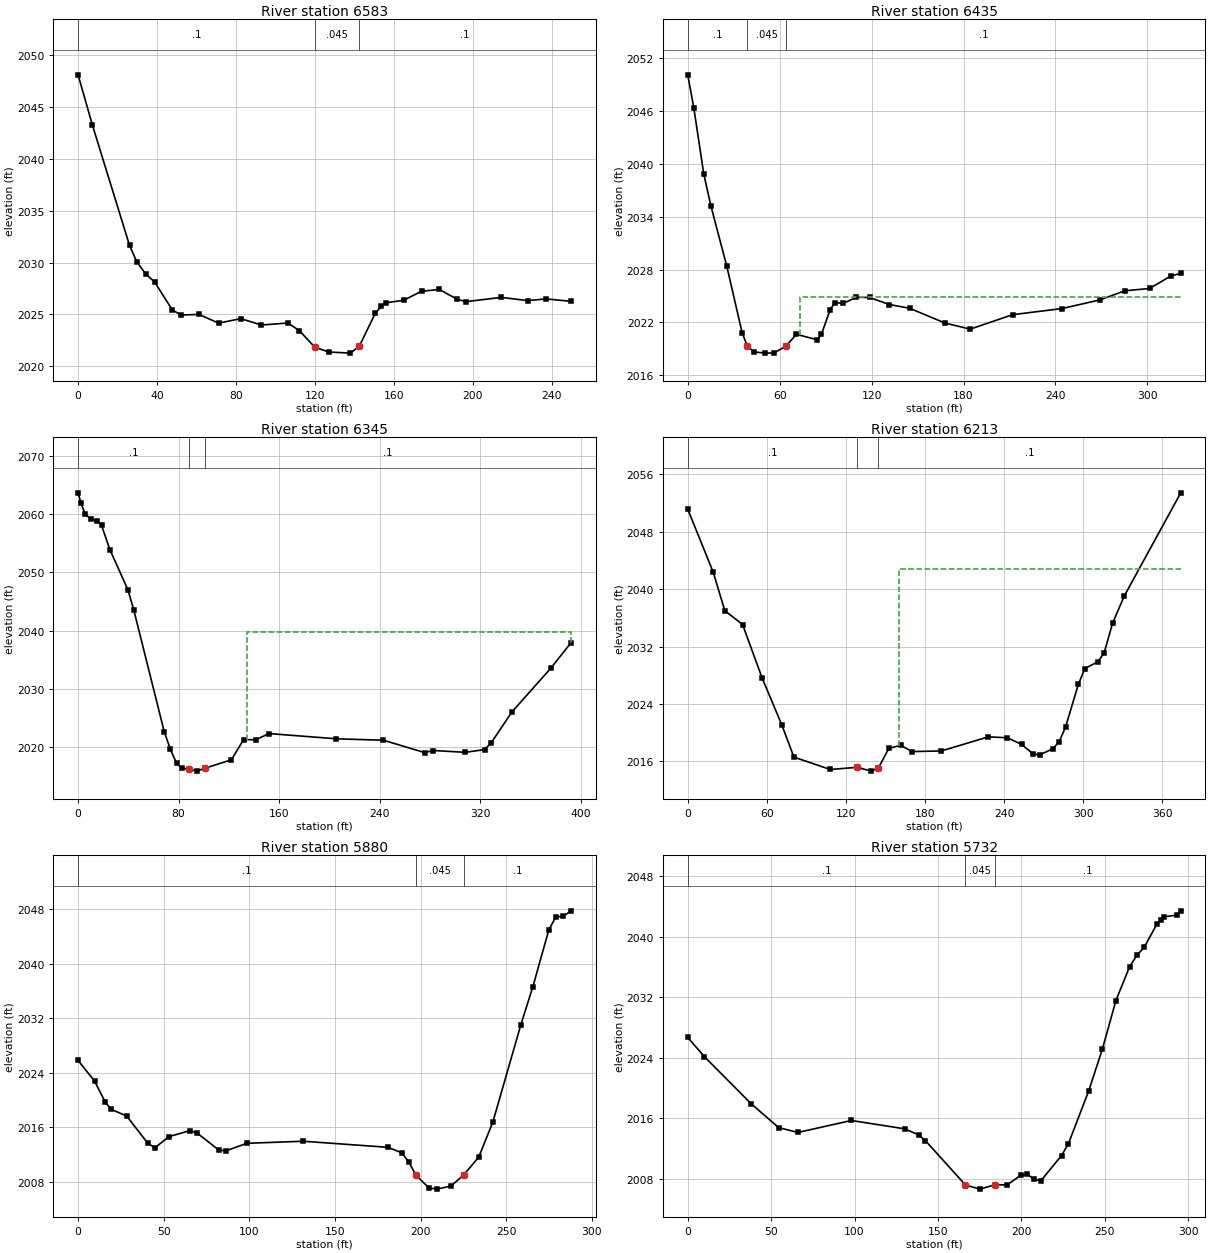
Type RM Length L Ch R = 1 ,6583    ,149.8,148.1,142.2
XS GIS Cut Line= 2
2163263.32418521622210.7628080262163378.68168538622432.488912258
#Sta/Elev= 30
       0 2048.08     7.2 2043.28    26.1 2031.64    29.8 2030.05    34.3 2028.89
    38.8 2028.12    47.8 2025.42    52.3 2024.94    61.3    2025    71.2 2024.16
    82.5 2024.59    92.9 2023.98   106.4 2024.17   112.2 2023.43     120 2021.84
     127 2021.38     138 2021.27   142.5 2021.92   150.7 2025.13   153.7 2025.77
     156 2026.12     165 2026.36   174.1 2027.23   183.1  2027.4   192.2 2026.46
   196.6 2026.23   214.6 2026.64   227.8 2026.33   237.2 2026.49   249.9 2026.26
#Mann= 3 ,-1,0
       0      .1       0     120    .045       0   142.5      .1       0
Bank Sta=120,142.5
XS Rating Curve= 0 ,0
Exp/Cntr(USF)=0,0
Exp/Cntr=0.3,0.1

Type RM Length L Ch R = 1 ,6435    ,90.1,90,90.6
XS GIS Cut Line= 3
 2163153.7405973 622325.111353332163237.85564621622433.987061611
2163397.93281043622525.228187896
#Sta/Elev= 30
       0 2050.14       4 2046.35    10.5 2038.83    15.2 2035.18    25.4 2028.44
    35.5 2020.81    38.9  2019.3    43.2 2018.63    50.6 2018.49    56.3 2018.51
   64.162019.287    70.9 2020.63    84.5 2020.01    87.3 2020.65      93 2023.44
    95.9 2024.22   101.6 2024.17   110.1 2024.83   118.7 2024.82   131.5 2024.02
   144.9 2023.59   167.9 2021.91   184.4 2021.22     212 2022.86   244.3 2023.56
   269.2 2024.55   285.3 2025.58   301.4 2025.84   315.2 2027.25   321.8 2027.56
#Mann= 3 ,-1,0
       0      .1       0    38.9    .045       0   64.16      .1       0
#XS Ineff= 2 , 0
                           73.16          2024.9
Permanent Ineff=
       F       F
Bank Sta=38.9,64.16
XS Rating Curve= 0 ,0
Exp/Cntr(USF)=0,0
Exp/Cntr=0.3,0.1

Type RM Length L Ch R = 1 ,6345    ,128.7,131.9,133.4
XS GIS Cut Line= 3
2163065.56847062622348.5925484942163167.44262662622496.909334434
2163306.77051644622657.211315196
#Sta/Elev= 30
       0 2063.61     2.3 2061.89     5.6 2059.96    10.4 2059.07    15.3  2058.8
    18.7 2058.02    25.3 2053.88    39.7 2046.99    44.4 2043.49    68.6 2022.67
    73.5 2019.66    78.4 2017.27    82.8 2016.41    88.1 2016.36    94.4 2015.95
   100.7 2016.43     122 2017.89   131.7 2021.34   141.4 2021.33   151.9 2022.38
   205.4 2021.49     243 2021.24   275.7 2019.13   282.7 2019.48   308.2 2019.17
   323.4 2019.64   328.7 2020.79   345.1 2026.06   376.3 2033.61   392.3 2037.96
#Mann= 3 ,-1,0
       0      .1       0    88.1    .045       0   100.7      .1       0
#XS Ineff= 2 , 0
                          134.08          2039.7
Permanent Ineff=
       F       F
Bank Sta=88.1,100.7
XS Rating Curve= 0 ,0
Exp/Cntr(USF)=0,0
Exp/Cntr=0.3,0.1

Type RM Length L Ch R = 1 ,6213    ,322,333.3,339.3
XS GIS Cut Line= 3
2162978.02549741622399.8326674672163077.55366545622606.274237197
2163160.78451484 622724.69719792
#Sta/Elev= 30
       0 2051.12    19.3 2042.36    28.1    2037    41.6 2035.06    56.5 2027.58
    71.5 2021.03    80.5 2016.61   108.1 2014.89   128.5 2015.19   139.2 2014.66
   144.62015.093   152.5 2017.82   161.4 2018.25   170.4 2017.38   192.4 2017.47
     228 2019.43   242.5  2019.3   253.2 2018.38   262.1 2017.03     267 2016.93
   276.7 2017.76   281.6 2018.71   286.5 2020.78   296.3 2026.77   301.2 2028.94
     311 2029.87   315.8 2031.11   322.2 2035.25   331.1 2039.05   373.9 2053.39
#Mann= 3 ,-1,0
       0      .1       0   128.5    .045       0   144.6      .1       0
#XS Ineff= 2 , 0
                          160.45         2042.85
Permanent Ineff=
       F       F
Bank Sta=128.5,144.6
XS Rating Curve= 0 ,0
Exp/Cntr(USF)=0,0
Exp/Cntr=0.3,0.1

Type RM Length L Ch R = 1 ,5880    ,145.2,148.1,148.5
XS GIS Cut Line= 3
2162851.98668606622473.7218971842162889.44041989622619.042384418
2162917.90525759622753.875826181
#Sta/Elev= 30
       0 2025.83     9.6 2022.82      16 2019.66    19.4 2018.65    28.4 2017.67
    40.7 2013.67    44.9 2013.02    53.1 2014.65    65.5 2015.54    69.7 2015.14
    82.1 2012.69    86.2 2012.55    98.6 2013.67   131.6 2013.97   180.9 2013.08
     189 2012.28   193.1 2010.95   197.2 2009.03   204.8 2007.13   209.5 2006.94
   217.7 2007.39   225.1    2009     234 2011.65   242.2 2016.79   258.5 2031.03
   265.6 2036.68   274.9 2045.01     279 2046.92   283.1 2046.98   287.9  2047.8
#Mann= 3 ,-1,0
       0      .1       0   197.2    .045       0   225.1      .1       0
Bank Sta=197.2,225.1
XS Rating Curve= 0 ,0
Exp/Cntr(USF)=0,0
Exp/Cntr=0.3,0.1

Type RM Length L Ch R = 1 ,5732    ,102.6,103.5,99.9
XS GIS Cut Line= 3
2162748.61438071 622487.205241362162756.10512748622616.046085712
2162789.06441324 622779.34436518
#Sta/Elev= 30
       0 2026.69      10 2024.16      38 2017.94    54.5 2014.78    66.1 2014.14
    98.1 2015.72   130.1 2014.62   138.4 2013.82   142.5 2013.06   166.52007.195
   175.1 2006.65   184.32007.232   191.4  2007.2   199.6 2008.46   203.7 2008.61
   207.7 2007.93   211.8 2007.78   224.1 2011.08   228.2 2012.63   240.4 2019.63
   248.6 2025.15   256.7 2031.56   264.9 2036.03   269.3 2037.55   273.6 2038.59
   281.2 2041.64   283.8 2042.28   285.3 2042.64   293.4 2042.86   295.6 2043.43
#Mann= 3 ,-1,0
       0      .1       0   166.5    .045       0   184.3      .1       0
Bank Sta=166.5,184.3
XS Rating Curve= 0 ,0
Exp/Cntr(USF)=0,0
Exp/Cntr=0.3,0.1

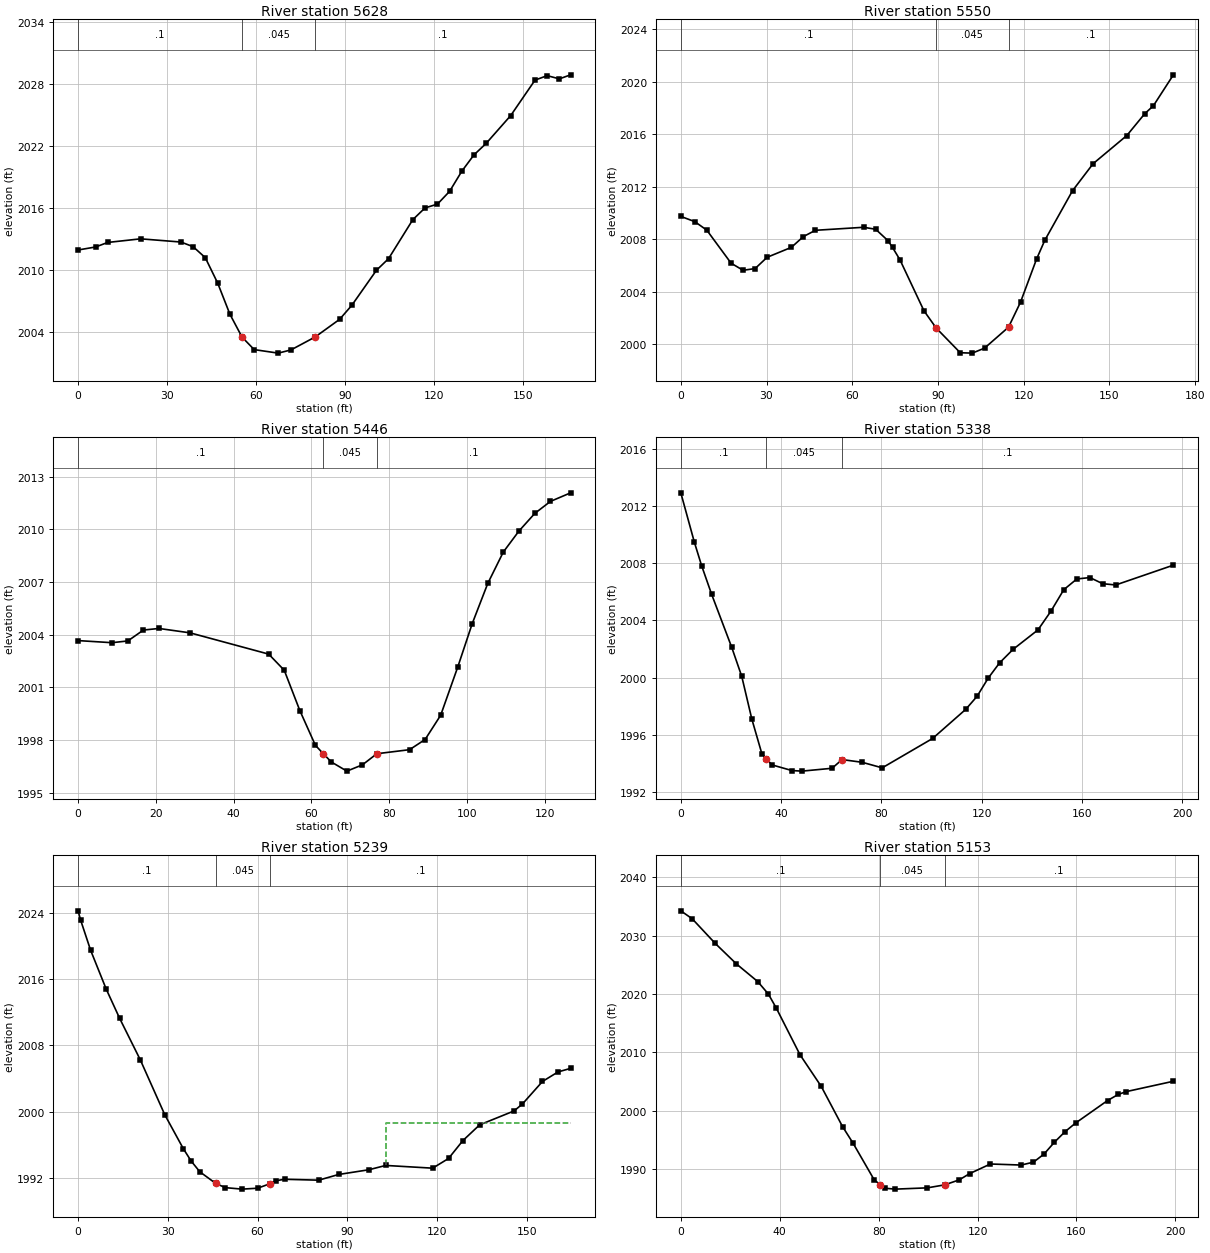
Type RM Length L Ch R = 1 ,5628    ,79.5,78.6,76.5
XS GIS Cut Line= 2
2162652.37016618622611.4634745832162691.72214052622772.851250744
#Sta/Elev= 30
       0 2011.91     5.9  2012.2      10 2012.64    21.1 2012.99    34.7 2012.68
    38.8 2012.23    42.9 2011.17    47.1  2008.7    51.2  2005.7    55.3 2003.48
    59.4 2002.27    67.5 2001.93    71.8 2002.24      80  2003.5    88.2  2005.2
    92.3 2006.55   100.6 2009.94   104.7 2011.07   112.9 2014.85     117 2015.98
   121.2 2016.35   125.3 2017.59   129.4 2019.53   133.5 2021.11   137.6 2022.22
   145.9 2024.92   154.1 2028.35   158.2 2028.78   162.3 2028.47   166.1 2028.86
#Mann= 3 ,-1,0
       0      .1       0    55.3    .045       0      80      .1       0
Bank Sta=55.3,80
XS Rating Curve= 0 ,0
Exp/Cntr(USF)=0,0
Exp/Cntr=0.3,0.1

Type RM Length L Ch R = 1 ,5550    ,100.4,103.5,106.5
XS GIS Cut Line= 2
2162562.84386095622608.5553389472162618.27538701622771.853618416
#Sta/Elev= 30
       0 2009.73     4.9 2009.33     9.1 2008.68    17.6 2006.16    21.8 2005.62
      26 2005.75    30.2 2006.61    38.7 2007.37    42.9 2008.19    47.1 2008.67
      64  2008.9    68.2 2008.75    72.5 2007.88    74.1 2007.36    76.7 2006.42
    85.1 2002.53    89.4 2001.21    97.8 1999.33     102  1999.3   106.3 1999.68
   114.7 2001.28   118.9 2003.19   124.5 2006.47   127.4 2007.91   137.1 2011.69
   144.3 2013.75   156.1  2015.9   162.4 2017.57   165.4 2018.17   172.4 2020.53
#Mann= 3 ,-1,0
       0      .1       0    89.4    .045       0   114.7      .1       0
Bank Sta=89.4,114.7
XS Rating Curve= 0 ,0
Exp/Cntr(USF)=0,0
Exp/Cntr=0.3,0.1

Type RM Length L Ch R = 1 ,5446    ,106.2,107.8,103.8
XS GIS Cut Line= 2
2162489.43454266622656.4961182412162502.91788683622782.340663886
#Sta/Elev= 26
       0 2003.67     8.7 2003.55    12.8 2003.65    16.8 2004.27    20.8 2004.36
    28.8 2004.11      49  2002.9      53 2001.98      57 1999.69      61 1997.71
      631997.239    65.1 1996.76    69.1 1996.24    73.1  1996.6    76.81997.231
    85.2 1997.46    89.2 1998.04    93.2 1999.42    97.6 2002.17   101.3 2004.63
   105.3 2006.92   109.3 2008.71   113.3  2009.9   117.4 2010.91   121.4 2011.59
   126.6 2012.08
#Mann= 3 ,-1,0
       0      .1       0      63    .045       0    76.8      .1       0
Bank Sta=63,76.8
XS Rating Curve= 0 ,0
Exp/Cntr(USF)=0,0
Exp/Cntr=0.3,0.1

Type RM Length L Ch R = 1 ,5338    ,106,99.1,81.6
XS GIS Cut Line= 4
2162393.09228131622664.905910014 2162397.4621714622767.478457233
2162409.07044649622790.0501032572162452.30895746622842.971047342
#Sta/Elev= 30
       0 2012.95     5.4 2009.49     8.3 2007.84    12.3 2005.83    20.3 2002.12
    24.3 2000.08    28.3  1997.1    32.3 1994.67    34.11994.315    36.3 1993.88
    44.3 1993.48    48.3 1993.44    60.3 1993.64    64.3 1994.25    72.3 1994.06
    80.3 1993.67   100.4 1995.73   113.6 1997.77   118.1 1998.68   122.6 1999.97
   127.1 2001.03   132.5 2001.98   142.4 2003.34   147.6 2004.66   152.7 2006.16
   157.9 2006.91   163.1 2007.01   168.2 2006.58   173.4 2006.49   196.4 2007.88
#Mann= 3 ,-1,0
       0      .1       0    34.1    .045       0    64.3      .1       0
Bank Sta=34.1,64.3
XS Rating Curve= 0 ,0
Exp/Cntr(USF)=0,0
Exp/Cntr=0.3,0.1

Type RM Length L Ch R = 1 ,5239    ,92.8,86.7,77
XS GIS Cut Line= 2
2162277.47409593622702.592732045 2162383.6311613622828.408513223
#Sta/Elev= 30
       0 2024.24      .9 2023.08     4.2 2019.48     9.4  2014.8    13.9 2011.26
    20.8 2006.25      29 1999.61    35.2 1995.51    37.8 1994.03    40.7 1992.73
      461991.332    49.2 1990.82    54.8 1990.64      60 1990.75    64.31991.314
    66.2 1991.66      69 1991.83    80.4 1991.72    87.1 1992.41    97.2 1992.98
   102.8  1993.5   118.5 1993.17   123.8 1994.34   128.6  1996.5   134.2  1998.4
   145.7 2000.08   148.5 2000.92   155.2 2003.64   160.4 2004.79   164.6 2005.22
#Mann= 3 ,-1,0
       0      .1       0      46    .045       0    64.3      .1       0
#XS Ineff= 2 , 0
                          102.83         1998.62
Permanent Ineff=
       F       F
Bank Sta=46,64.3
XS Rating Curve= 0 ,0
Exp/Cntr(USF)=0,0
Exp/Cntr=0.3,0.1

Type RM Length L Ch R = 1 ,5153    ,86.8,87.1,86.5
XS GIS Cut Line= 2
2162179.18051689622780.2446594912162364.95538128622851.998972194
#Sta/Elev= 30
       0 2034.27     4.6 2032.91    13.9 2028.69    22.5 2025.16    31.1 2022.14
    35.4    2020    38.6  2017.6    48.2 2009.59    56.8 2004.15    65.4 1997.27
    69.7 1994.39    78.2 1988.14    80.61987.313    82.5 1986.69    86.8 1986.54
    99.7 1986.76   106.7 1987.27   112.6 1988.13   116.8  1989.2   125.2 1990.85
   137.6 1990.67   142.6 1991.16   146.9 1992.56   151.1 1994.59   155.4  1996.4
   159.7 1997.89   172.6 2001.74   176.9 2002.78   180.2 2003.27   199.2 2005.04
#Mann= 3 ,-1,0
       0      .1       0    80.6    .045       0   106.7      .1       0
Bank Sta=80.6,106.7
XS Rating Curve= 0 ,0
Exp/Cntr(USF)=0,0
Exp/Cntr=0.3,0.1

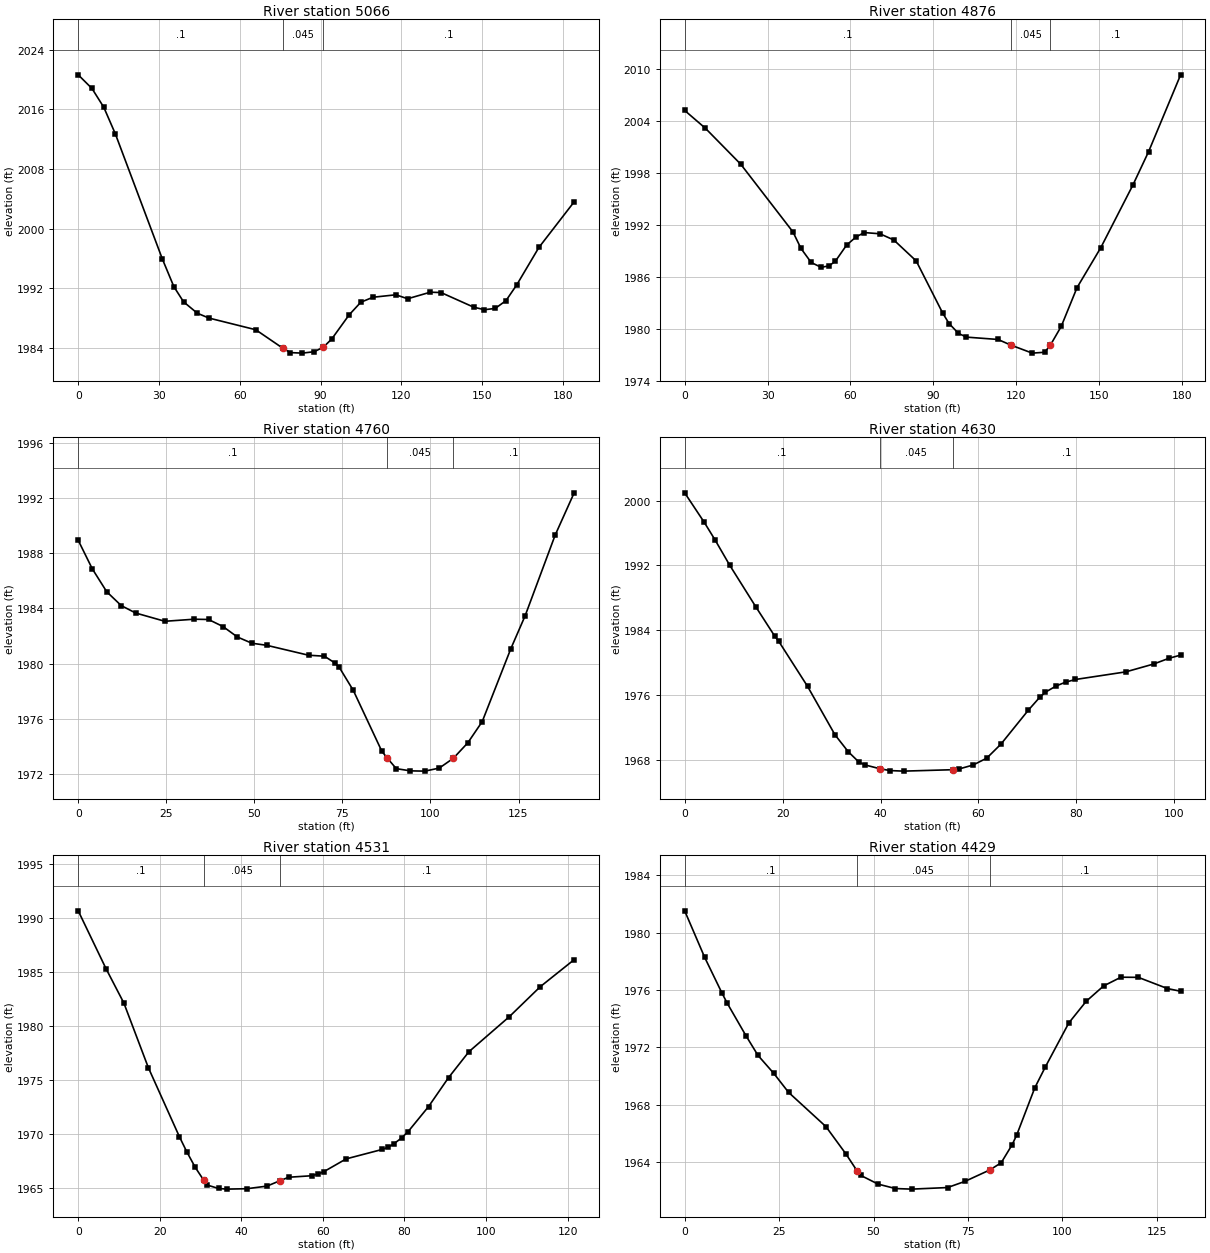
Type RM Length L Ch R = 1 ,5066    ,179.9,189.2,192.8
XS GIS Cut Line= 3
2162163.43464082622862.7394959072162281.20173614622912.208651296
2162337.43317915 622908.02631225
#Sta/Elev= 30
       0 2020.65     5.1 2018.82     9.5 2016.29    13.8 2012.71    31.2 1995.96
    35.5 1992.22    39.1 1990.18    44.2 1988.65    48.5    1988    65.9 1986.43
      761983.938    78.8 1983.36    83.2 1983.29    87.6 1983.48      91 1984.09
    94.1 1985.18   100.6 1988.44   104.9 1990.12   109.4 1990.79   117.9 1991.12
   122.3 1990.59   130.7 1991.47   134.7 1991.42   146.8 1989.46   150.8 1989.12
   154.8 1989.29   158.8 1990.34   162.8 1992.46     171 1997.47   184.1  2003.6
#Mann= 3 ,-1,0
       0      .1       0      76    .045       0      91      .1       0
Bank Sta=76,91
XS Rating Curve= 0 ,0
Exp/Cntr(USF)=0,0
Exp/Cntr=0.3,0.1

Type RM Length L Ch R = 1 ,4876    ,108.5,116.1,120.8
XS GIS Cut Line= 5
2162153.65489601622976.4733958592162206.70271902623019.098056571
2162258.82887379623088.1971725532162268.93248095623098.364026924
2162276.65872652623105.590275159
#Sta/Elev= 30
       0 2005.26     7.5  2003.2    20.3 1999.04    39.2 1991.21    42.1  1989.3
    45.8 1987.68    49.4 1987.12    52.2 1987.29    54.5 1987.81    58.6 1989.69
      62 1990.63      65 1991.14    70.7    1991    75.7 1990.28    83.8 1987.86
    93.4 1981.82    95.7 1980.62    99.1 1979.48     102 1979.05   113.4 1978.78
  117.941978.145   125.8  1977.2   130.3  1977.3   132.41978.143   136.3  1980.3
     142 1984.77   150.6 1989.39   162.2 1996.62   167.9 2000.49   179.5 2009.38
#Mann= 3 ,-1,0
       0      .1       0  117.94    .045       0   132.4      .1       0
Bank Sta=117.94,132.4
XS Rating Curve= 0 ,0
Exp/Cntr(USF)=0,0
Exp/Cntr=0.3,0.1

Type RM Length L Ch R = 1 ,4760    ,137.3,130.8,121.2
XS GIS Cut Line= 3
2162144.26564915623005.3388849432162128.08563614623068.710602572
2162141.56898032623142.868995542
#Sta/Elev= 30
       0 1988.93       4 1986.86     8.1  1985.2    12.2  1984.2    16.3 1983.66
    24.6 1983.06    32.9 1983.21      37 1983.19    41.1 1982.68    45.2 1981.92
    49.3 1981.47    53.5 1981.32    65.4  1980.6    69.9 1980.53    72.8 1980.05
      74 1979.77    78.1 1978.05    86.2 1973.64    87.81973.129    90.3 1972.38
    94.3 1972.22    98.4  1972.2   102.5 1972.42   106.5 1973.13   110.6 1974.25
   114.7 1975.79   122.8 1981.06   126.9 1983.47   135.4  1989.3   140.8 1992.37
#Mann= 3 ,-1,0
       0      .1       0    87.8    .045       0   106.5      .1       0
Bank Sta=87.8,106.5
XS Rating Curve= 0 ,0
Exp/Cntr(USF)=0,0
Exp/Cntr=0.3,0.1

Type RM Length L Ch R = 1 ,4630    ,99.6,98.9,97.7
XS GIS Cut Line= 2
2161985.16218787623109.1606351012162062.01724968623175.229021565
#Sta/Elev= 30
       0 2000.95       4 1997.31     6.2 1995.15     9.2 1992.02    14.5 1986.92
    18.4 1983.27    19.2 1982.65    25.1 1977.08    30.7 1971.11    33.4 1969.03
    35.6 1967.74    36.8  1967.4    39.81966.936    41.9  1966.7    44.7 1966.63
    54.81966.806      56 1966.89    58.9 1967.38    61.7 1968.23    64.6 1969.96
    70.2 1974.15    72.5 1975.72    73.7 1976.37    75.9 1977.14    77.8  1977.6
    79.8 1977.93    90.1 1978.87    95.8 1979.84    98.9 1980.54   101.3 1980.94
#Mann= 3 ,-1,0
       0      .1       0    39.8    .045       0    54.8      .1       0
Bank Sta=39.8,54.8
XS Rating Curve= 0 ,0
Exp/Cntr(USF)=0,0
Exp/Cntr=0.3,0.1

Type RM Length L Ch R = 1 ,4531    ,102.6,101.2,100.6
XS GIS Cut Line= 2
2161930.67480873623194.5932355992162029.10322122623266.054959734
#Sta/Elev= 30
       0 1990.62     6.8 1985.28    11.2 1982.08    17.2  1976.1    24.8 1969.72
    26.6 1968.33    28.7 1966.87    30.8 1965.67    31.6 1965.24    34.4 1964.92
    36.5 1964.86    41.4  1964.9    46.3 1965.14    49.4 1965.63    51.6 1965.96
    57.3  1966.1    58.9 1966.28    60.2 1966.47    65.7 1967.66    74.5 1968.53
      76 1968.74    77.4 1969.06    79.3  1969.6    80.9 1970.19    85.9  1972.5
    90.8 1975.18    95.8 1977.58   105.7 1980.82   113.3  1983.6   121.6  1986.1
#Mann= 3 ,-1,0
       0      .1       0    30.8    .045       0    49.4      .1       0
Bank Sta=30.8,49.4
XS Rating Curve= 0 ,0
Exp/Cntr(USF)=0,0
Exp/Cntr=0.3,0.1

Type RM Length L Ch R = 1 ,4429    ,88.1,85.6,83.2
XS GIS Cut Line= 2
2161867.58214346623279.645187935 2161981.9473623623344.162567769
#Sta/Elev= 30
       0 1981.53     5.3 1978.28     9.9 1975.78    11.3 1975.07    16.2 1972.83
    19.4 1971.45    23.6 1970.19    27.5 1968.87    37.4 1966.48    42.7 1964.57
    45.6 1963.41    46.6 1963.08    51.2 1962.47    55.8 1962.16    60.1 1962.12
    69.6 1962.23    74.2 1962.66    80.8 1963.46    83.8 1963.96    86.7 1965.22
    87.9 1965.89    92.7 1969.19    95.5 1970.65   101.7 1973.71   106.3 1975.22
   110.9 1976.29   115.5  1976.9   120.1 1976.89   127.8 1976.11   131.3 1975.92
#Mann= 3 ,-1,0
       0      .1       0    45.6    .045       0    80.8      .1       0
Bank Sta=45.6,80.8
XS Rating Curve= 0 ,0
Exp/Cntr(USF)=0,0
Exp/Cntr=0.3,0.1