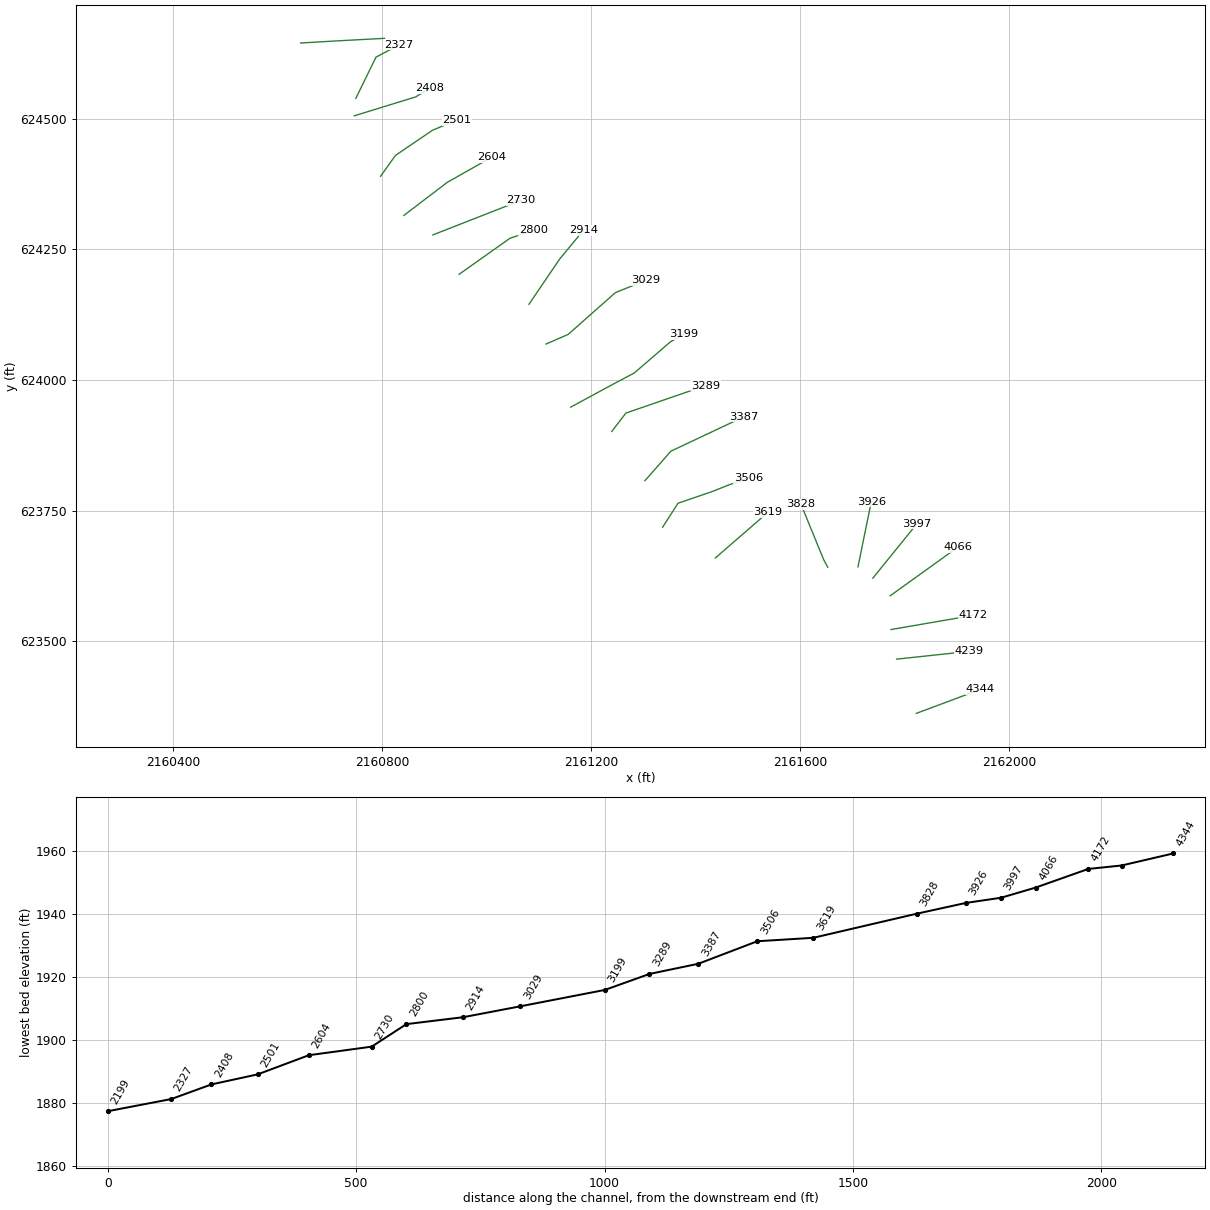
HEC-RAS study HOWELLFK.prj: HOWELLFK

--- HOWELLFK.g01 (geometry) --- (continued)

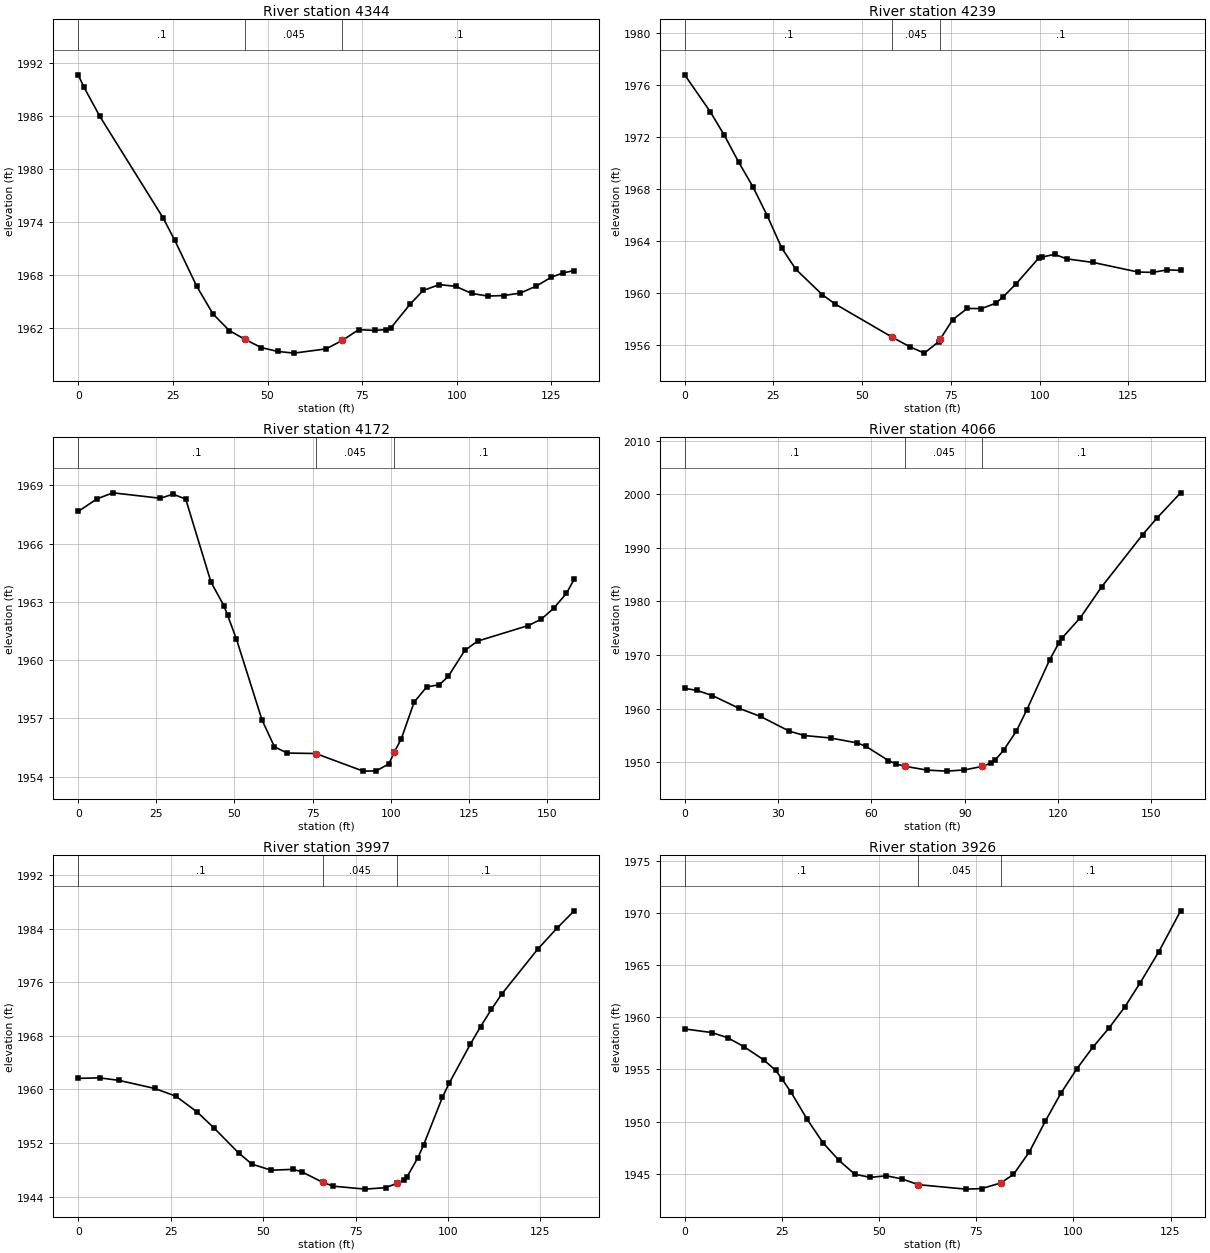
Type RM Length L Ch R = 1 ,4344    ,104.3,104.4,97.5
XS GIS Cut Line= 2
2161822.80805532623361.7867033862161945.50648733623407.630073585
#Sta/Elev= 30
       0 1990.63     1.5 1989.25     5.7 1985.95    22.4  1974.5    25.5 1971.96
    31.3 1966.77    35.6 1963.64    39.9 1961.77      44 1960.78    48.4 1959.84
    52.7 1959.41      57 1959.22    65.5  1959.7    69.8 1960.67    74.1 1961.87
    78.3 1961.78    81.4 1961.88    82.6 1962.07    87.6 1964.71    91.1 1966.29
    95.4 1966.95    99.7 1966.76   103.9 1965.96   108.2 1965.66   112.4 1965.72
   116.8    1966     121 1966.79   124.9 1967.77     128 1968.27     131 1968.53
#Mann= 3 ,-1,0
       0      .1       0      44    .045       0    69.8      .1       0
Bank Sta=44,69.8
XS Rating Curve= 0 ,0
Exp/Cntr(USF)=0,0
Exp/Cntr=0.3,0.1

Type RM Length L Ch R = 1 ,4239    ,63.8,66.9,69.6
XS GIS Cut Line= 2
2161785.05469163623465.6084535432161923.93313665623480.440132137
#Sta/Elev= 30
       0 1976.81     7.2 1973.97    11.2 1972.14    15.2 1970.09    19.2  1968.2
    23.3 1965.94    27.3 1963.49    31.3 1961.84    38.8 1959.87    42.4 1959.16
    58.51956.598    63.5 1955.86    67.5 1955.38    71.5 1956.25      721956.464
    75.5 1957.96    79.6 1958.82    83.6 1958.81    87.6 1959.22    89.7 1959.71
    93.3  1960.7    99.7 1962.69   100.6 1962.77   104.2 1962.99   107.6 1962.64
   115.1 1962.36   127.8 1961.62   131.9  1961.6   135.9 1961.79   139.7 1961.75
#Mann= 3 ,-1,0
       0      .1       0    58.5    .045       0      72      .1       0
Bank Sta=58.5,72
XS Rating Curve= 0 ,0
Exp/Cntr(USF)=0,0
Exp/Cntr=0.3,0.1

Type RM Length L Ch R = 1 ,4172    ,96.7,106.2,112.2
XS GIS Cut Line= 2
2161774.26801629623522.2384990842161930.67480873623549.205187437
#Sta/Elev= 30
       0 1967.65       6  1968.3    11.1 1968.61    26.3 1968.33    30.3 1968.54
    34.4 1968.29    42.5 1964.01    46.6 1962.81    47.8 1962.31    50.6  1961.1
    58.8 1956.93    62.8 1955.54    66.9 1955.22      761955.196    91.2 1954.29
    95.3  1954.3    99.4 1954.66   101.1 1955.25   103.4 1955.96   107.5 1957.84
   111.5 1958.62   115.6 1958.74   118.4 1959.16   123.7  1960.5   127.8 1960.98
     144 1961.78   148.1  1962.1   152.1 1962.66   156.2 1963.43   158.7 1964.16
#Mann= 3 ,-1,0
       0      .1       0      76    .045       0   101.1      .1       0
Bank Sta=76,101.1
XS Rating Curve= 0 ,0
Exp/Cntr(USF)=0,0
Exp/Cntr=0.3,0.1

Type RM Length L Ch R = 1 ,4066    ,64.7,69.4,73.9
XS GIS Cut Line= 2
2161772.91968187 623586.958551132161902.35978596623679.993625947
#Sta/Elev= 30
       0 1963.81       4  1963.4     8.9 1962.46    17.5 1960.07    24.4 1958.55
    33.6 1955.82    38.5    1955    46.9 1954.54    55.5 1953.61    58.2    1953
    65.5 1950.33      68 1949.68   70.951949.249    77.9 1948.55    84.2 1948.36
    89.9 1948.58    95.6 1949.24    98.5 1949.87    99.8 1950.43   102.5 1952.25
   106.6 1955.82     110 1959.83   117.3 1969.12   120.3  1972.3   121.4 1973.26
   127.2    1977     134 1982.72   147.2 1992.47   151.8 1995.57   159.4 2000.27
#Mann= 3 ,-1,0
       0      .1       0   70.95    .045       0    95.6      .1       0
Bank Sta=70.95,95.6
XS Rating Curve= 0 ,0
Exp/Cntr(USF)=0,0
Exp/Cntr=0.3,0.1

Type RM Length L Ch R = 1 ,3997    ,63.1,70.3,77.7
XS GIS Cut Line= 2
2161739.60402482623620.6504329932161824.02208022623724.813000953
#Sta/Elev= 30
       0 1961.66     5.8 1961.73      11 1961.36    20.7 1960.15    26.4    1959
    32.1 1956.67    36.7 1954.27    43.4 1950.52      47 1948.86    52.2 1947.96
    58.1 1948.09    60.5 1947.71    66.2 1946.13      69 1945.58    77.6 1945.14
    83.1 1945.36    86.1 1945.98    88.2 1946.53    88.9 1946.97    91.8 1949.77
    93.4 1951.74    98.5 1958.87   100.3 1960.93     106 1966.72   108.8 1969.38
   111.7 1971.93   114.5 1974.21   124.2 1980.89   129.4 1984.02   134.1 1986.64
#Mann= 3 ,-1,0
       0      .1       0    66.2    .045       0    86.1      .1       0
Bank Sta=66.2,86.1
XS Rating Curve= 0 ,0
Exp/Cntr(USF)=0,0
Exp/Cntr=0.3,0.1

Type RM Length L Ch R = 1 ,3926    ,90.2,98.7,108.1
XS GIS Cut Line= 2
2161711.16648946623642.2949345942161736.65000995623767.285535109
#Sta/Elev= 30
       0 1958.89       7 1958.54    11.1 1958.04    15.2  1957.2    20.3 1955.93
    23.4 1954.92    25.1 1954.05    27.4 1952.79    31.5 1950.22    35.6 1947.95
    39.7 1946.27    43.8 1944.93    47.8 1944.64    51.9 1944.79      56 1944.48
    60.1 1943.94    72.3 1943.51    76.4 1943.56    81.3  1944.1    84.6 1944.92
    88.7  1947.1    92.8 1950.04    96.8 1952.72   100.9 1955.06     105 1957.13
   109.1 1958.94   113.2 1960.98   117.2 1963.32     122 1966.31   127.6 1970.23
#Mann= 3 ,-1,0
       0      .1       0    60.1    .045       0    81.3      .1       0
Bank Sta=60.1,81.3
XS Rating Curve= 0 ,0
Exp/Cntr(USF)=0,0
Exp/Cntr=0.3,0.1

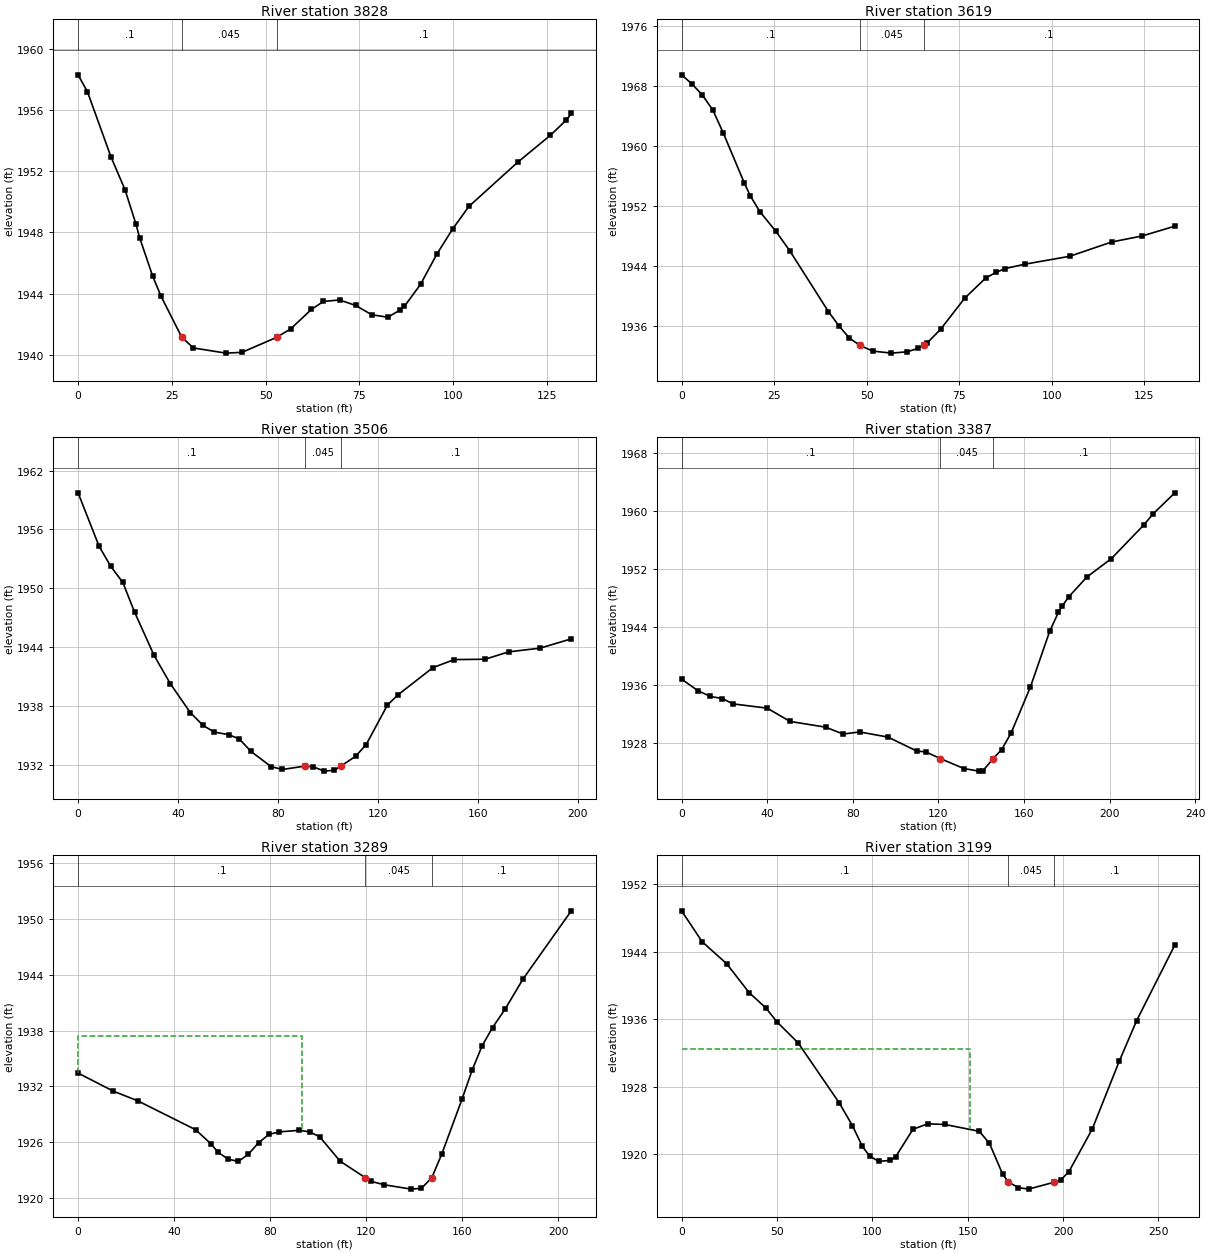
Type RM Length L Ch R = 1 ,3828    ,215.6,208.9,195.5
XS GIS Cut Line= 3
2161653.36886991623641.4703873782161645.49223895623655.911590212
2161601.95140163623762.431531205
#Sta/Elev= 30
       0 1958.31     2.5  1957.2     8.8 1952.92    12.5  1950.8    15.4 1948.57
    16.4 1947.66    19.9 1945.13    22.1 1943.83    27.6 1941.16    30.7 1940.44
    39.4  1940.1    43.7 1940.15    52.9 1941.13    56.7 1941.69    62.2 1942.96
    65.4 1943.48    69.7 1943.58      74 1943.22    78.3 1942.61    82.6 1942.45
    85.9 1942.93      87 1943.16    91.3  1944.6    95.6 1946.56    99.9 1948.24
   104.2  1949.7   117.2 1952.59   125.9 1954.35   130.2 1955.36   131.5 1955.78
#Mann= 3 ,-1,0
       0      .1       0    27.6    .045       0    52.9      .1       0
Bank Sta=27.6,52.9
XS Rating Curve= 0 ,0
Exp/Cntr(USF)=0,0
Exp/Cntr=0.3,0.1

Type RM Length L Ch R = 1 ,3619    ,118.1,112.6,109
XS GIS Cut Line= 2
2161438.12876989623659.2839482562161538.84935089623746.656018519
#Sta/Elev= 30
       0 1969.49     2.8 1968.28     5.6 1966.81     8.5 1964.75    11.3  1961.7
      17 1955.03    18.6 1953.34    21.2 1951.24    25.5 1948.63    29.2 1946.08
    39.7 1937.94    42.5 1936.07    45.3 1934.45    48.2 1933.44    51.7 1932.69
    56.7 1932.42      61  1932.6    63.9 1933.05    65.41933.437    66.3 1933.74
      70  1935.6    76.5 1939.73    82.2 1942.43      85 1943.18    87.4 1943.68
    92.7 1944.26   104.9 1945.32   116.2 1947.22   124.5 1948.03   133.3 1949.33
#Mann= 3 ,-1,0
       0      .1       0    48.2    .045       0    65.4      .1       0
Bank Sta=48.2,65.4
XS Rating Curve= 0 ,0
Exp/Cntr(USF)=0,0
Exp/Cntr=0.3,0.1

Type RM Length L Ch R = 1 ,3506    ,111.8,118.9,120.5
XS GIS Cut Line= 5
2161337.17201343623718.1497993792161366.63005771623764.005743728
2161433.01661651623786.7328811392161464.05428435623799.138313729
2161501.13273175623812.264829173
#Sta/Elev= 30
       0 1959.73     8.4 1954.28    13.1 1952.22    17.9 1950.59    22.6 1947.56
    30.4 1943.15    36.9 1940.26    44.9 1937.31      50    1936    54.5 1935.31
    60.4 1935.05    64.6 1934.59    69.2 1933.34    77.3 1931.78    81.8  1931.5
    90.71931.837    94.2 1931.77    98.4 1931.33   102.6 1931.42  105.261931.861
   111.1 1932.85   115.3 1934.04   123.8 1938.07   128.1 1939.13     142 1941.89
   150.5 1942.71   162.9 1942.75   172.3  1943.5   184.9 1943.88   197.4 1944.83
#Mann= 3 ,-1,0
       0      .1       0    90.7    .045       0  105.26      .1       0
Bank Sta=90.7,105.26
XS Rating Curve= 0 ,0
Exp/Cntr(USF)=0,0
Exp/Cntr=0.3,0.1

Type RM Length L Ch R = 1 ,3387    ,99,98.3,96.2
XS GIS Cut Line= 3
2161303.25834008623807.1524450922161353.14671353623863.782490633
2161493.37349296623929.850877097
#Sta/Elev= 30
       0 1936.84     7.8 1935.23    13.5 1934.46    19.1 1934.17      24 1933.44
      40 1932.85    50.7 1931.02    67.3 1930.23    75.5 1929.28    83.2 1929.57
    96.5 1928.86   109.8 1926.95   114.2 1926.81   120.9  1925.9   131.9 1924.53
   138.9 1924.17   140.7 1924.19   145.61925.879   149.6 1927.15     154 1929.43
     163 1935.76     172 1943.43   176.1 1946.06     178 1946.98     181 1948.22
   189.4 1950.93   200.8 1953.45   215.9 1958.07   220.3 1959.62   230.5 1962.53
#Mann= 3 ,-1,0
       0      .1       0   120.9    .045       0   145.6      .1       0
Bank Sta=120.9,145.6
XS Rating Curve= 0 ,0
Exp/Cntr(USF)=0,0
Exp/Cntr=0.3,0.1

Type RM Length L Ch R = 1 ,3289    ,82.1,89.6,94.6
XS GIS Cut Line= 3
2161239.88662245623901.535854326 2161266.8533108623936.592549185
2161419.21509999623989.177591472
#Sta/Elev= 30
       0 1933.43    14.7 1931.48    24.8 1930.45    48.9 1927.34    55.2 1925.85
    58.3  1924.9    62.6 1924.15    66.8 1923.93    70.9 1924.69    75.2 1925.94
    79.5 1926.83    83.7  1927.1    92.2 1927.27    96.4  1927.1   100.6 1926.58
   109.1 1923.95   119.6 1922.17   121.8 1921.79   127.5 1921.41   138.7 1920.94
     143 1921.03   147.31922.172   151.4 1924.68   159.9 1930.63   164.1 1933.75
   168.3 1936.39   172.6 1938.33   177.9 1940.34   185.3 1943.56   205.4 1950.89
#Mann= 3 ,-1,0
       0      .1       0   119.6    .045       0   147.3      .1       0
#XS Ineff= 2 , 0
           93.24 1937.37
Permanent Ineff=
       F       F
Bank Sta=119.6,147.3
XS Rating Curve= 0 ,0
Exp/Cntr(USF)=0,0
Exp/Cntr=0.3,0.1

Type RM Length L Ch R = 1 ,3199    ,167.8,170.1,169
XS GIS Cut Line= 5
2161161.36623457623948.0399971072161236.92659758 623989.01948564
2161283.03332381 624013.447610992161351.79837911624072.774325366
2161377.41673305624087.606003959
#Sta/Elev= 30
       0 1948.85    10.8 1945.18    23.6 1942.59    35.4 1939.16    44.1 1937.36
    50.1 1935.67    61.1  1933.2    82.6 1926.11    89.6 1923.38    94.8 1920.93
    98.7 1919.76   103.4 1919.16   109.2 1919.27   112.2 1919.69   121.3 1922.96
     129 1923.61   138.1 1923.53   156.1 1922.72   161.4 1921.29   168.3 1917.66
   171.3 1916.71   176.6 1916.05   181.9 1915.87   195.5  1916.7     199 1917.01
     203 1917.91   215.3 1922.99   229.5 1931.05   238.6 1935.85   258.6  1944.8
#Mann= 3 ,-1,0
       0      .1       0   171.3    .045       0   195.5      .1       0
#XS Ineff= 2 , 0
           151.1 1932.46
Permanent Ineff=
       F       F
Bank Sta=171.3,195.5
XS Rating Curve= 0 ,0
Exp/Cntr(USF)=0,0
Exp/Cntr=0.3,0.1

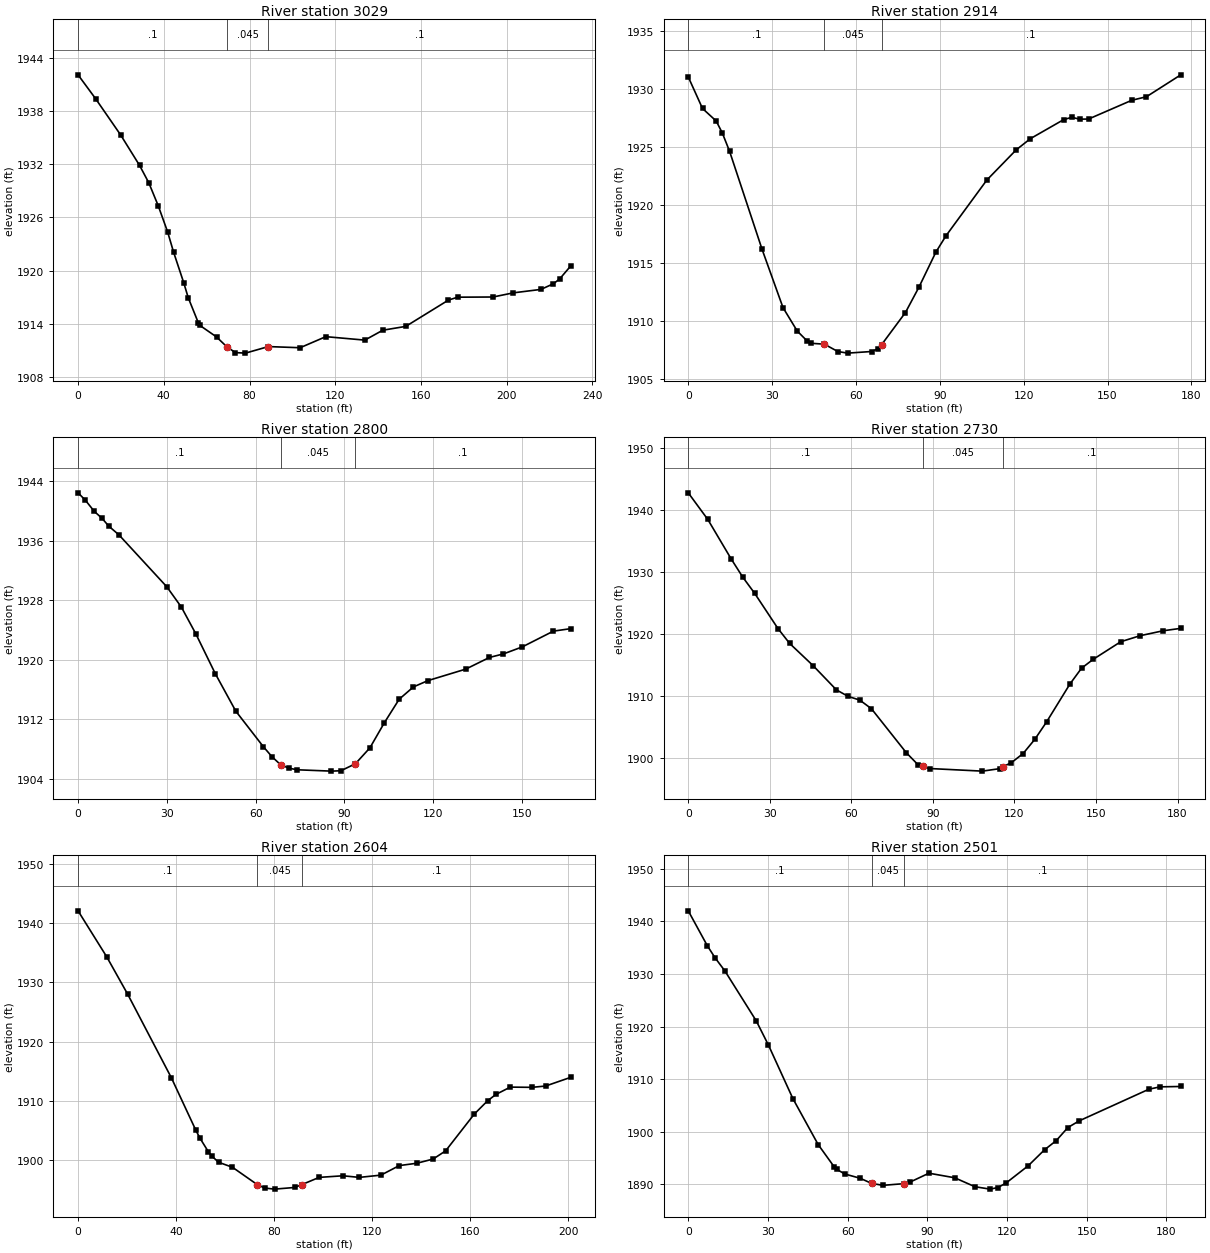
Type RM Length L Ch R = 1 ,3029    ,110.3,115.1,118.1
XS GIS Cut Line= 4
2161113.88393648624068.7396577242161156.26909991624087.162175116
2161246.56706684624167.030612181 2161304.8670062624190.865968768
#Sta/Elev= 30
       0 1942.11     8.2 1939.41    19.9 1935.31    28.7 1931.88      33 1929.92
    37.4 1927.33    41.8 1924.36    44.6 1922.06    49.3 1918.63    51.4 1916.94
    56.1 1914.11    56.8 1913.81    64.6  1912.5    69.4 1911.39    73.4 1910.73
    78.1 1910.67    88.8 1911.41   103.6 1911.28   115.6 1912.53   133.8 1912.14
   142.2 1913.26   152.9 1913.69   172.8 1916.66   177.1 1916.99   193.6 1917.01
   203.1 1917.48     216 1917.87   221.8 1918.51   224.7 1919.05   229.8  1920.5
#Mann= 3 ,-1,0
       0      .1       0    69.4    .045       0    88.8      .1       0
Bank Sta=69.4,88.8
XS Rating Curve= 0 ,0
Exp/Cntr(USF)=0,0
Exp/Cntr=0.3,0.1

Type RM Length L Ch R = 1 ,2914    ,121.8,114.3,108.8
XS GIS Cut Line= 3
2161081.33325735624144.8944799442161140.25042863624231.677880883
2161185.63257407624286.614162212
#Sta/Elev= 30
       0 1931.01     5.1 1928.29      10 1927.21    12.2 1926.17    14.8 1924.59
    26.4 1916.16    33.9 1911.13      39 1909.11    42.6 1908.24    43.9 1908.06
    48.7 1907.98    53.5 1907.35      57 1907.21    65.6 1907.35      68  1907.6
    69.2 1907.95    77.7 1910.71    82.5 1912.88    88.6 1915.92    92.2 1917.32
   106.8 1922.12   117.3 1924.72   122.4 1925.69   134.3 1927.33   137.2 1927.53
     140 1927.37   143.2 1927.38   158.7    1929   163.9  1929.3   176.2 1931.19
#Mann= 3 ,-1,0
       0      .1       0    48.7    .045       0    69.2      .1       0
Bank Sta=48.7,69.2
XS Rating Curve= 0 ,0
Exp/Cntr(USF)=0,0
Exp/Cntr=0.3,0.1

Type RM Length L Ch R = 1 ,2800    ,74.1,69.7,65.9
XS GIS Cut Line= 3
2160947.70095233624202.363459159 2161044.9023805624271.168964491
2161089.68056651624286.459076787
#Sta/Elev= 30
       0 1942.46     2.4  1941.5     5.5 1939.96     8.1 1939.03    10.4 1937.97
    13.8 1936.81      30 1929.81    34.9 1927.09    39.8 1923.48    46.4  1918.1
    53.3 1913.08    62.6  1908.3    65.5 1906.96    68.4 1905.88    71.2 1905.41
    74.1 1905.19    85.6 1905.01    88.8 1905.06    93.7    1906    98.6 1908.14
   103.5 1911.53   108.5 1914.69   113.3 1916.34   118.2 1917.19     131 1918.74
     139 1920.31   143.7 1920.78   150.1 1921.73   160.6 1923.85   166.4 1924.18
#Mann= 3 ,-1,0
       0      .1       0    68.4    .045       0    93.7      .1       0
Bank Sta=68.4,93.7
XS Rating Curve= 0 ,0
Exp/Cntr(USF)=0,0
Exp/Cntr=0.3,0.1

Type RM Length L Ch R = 1 ,2730    ,123,126.6,133.5
XS GIS Cut Line= 2
2160897.46201193624277.7218697612161066.16109742624343.789526959
#Sta/Elev= 30
       0 1942.75     7.2 1938.45    15.8 1932.08    20.1 1929.12    24.4 1926.56
      33 1920.86    37.3 1918.46    45.9 1914.89    54.5 1910.97    58.8 1909.92
    63.1 1909.32    67.4 1907.92    80.2 1900.84    84.5  1898.9    86.3 1898.62
    88.8 1898.28   108.2 1897.86   114.6 1898.26   115.9  1898.6   118.9 1899.23
   123.2  1900.7   127.5 1902.99   131.8 1905.78   140.4  1911.9   144.7 1914.47
     149  1915.9   159.1 1918.73   166.2  1919.7   174.7  1920.5   181.2 1920.89
#Mann= 3 ,-1,0
       0      .1       0    86.3    .045       0   115.9      .1       0
Bank Sta=86.3,115.9
XS Rating Curve= 0 ,0
Exp/Cntr(USF)=0,0
Exp/Cntr=0.3,0.1

Type RM Length L Ch R = 1 ,2604    ,103,102.9,101.7
XS GIS Cut Line= 3
2160841.90205341624315.0134532172160924.90122036624378.278552502
2161009.06121482624425.872480404
#Sta/Elev= 30
       0 1942.06    11.7 1934.31    20.3 1927.97    38.1  1913.9    48.1 1905.04
    49.8  1903.7    53.2 1901.43    54.5 1900.74    57.4 1899.66      63 1898.83
   73.14  1895.9    76.2 1895.32    80.2 1895.14    88.4 1895.42    91.41895.916
    98.4 1897.12   108.1 1897.39   114.8 1897.12   123.6  1897.5   131.1 1899.11
   138.2  1899.5   144.9 1900.21     150 1901.59   161.7 1907.79   167.1 1910.02
   170.5  1911.1   176.4 1912.34   185.2  1912.3   190.8 1912.52     201 1913.98
#Mann= 3 ,-1,0
       0      .1       0   73.14    .045       0    91.4      .1       0
Bank Sta=73.14,91.4
XS Rating Curve= 0 ,0
Exp/Cntr(USF)=0,0
Exp/Cntr=0.3,0.1

Type RM Length L Ch R = 1 ,2501    ,96.3,93,90.9
XS GIS Cut Line= 4
2160797.30187504624389.9435032082160825.67707485624429.801034449
2160896.51931504  624477.91564152160943.39429407624497.652474777
#Sta/Elev= 30
       0 1942.01     7.2 1935.35    10.1 1933.07    13.8 1930.57    25.6 1921.07
    30.2 1916.45    39.4 1906.27    48.9 1897.54    54.9 1893.32      56  1892.8
    58.9 1891.94    64.7 1891.13      691890.155    73.3 1889.78    81.21890.103
    83.4 1890.38    90.6 1892.09   100.3 1891.22   107.9 1889.52   113.6 1889.06
   116.5 1889.35   119.6 1890.21     128 1893.52   134.1 1896.54   138.5 1898.28
   142.9 1900.78   147.2 1902.06   173.4 1908.07   177.6 1908.52   185.4 1908.59
#Mann= 3 ,-1,0
       0      .1       0      69    .045       0    81.2      .1       0
Bank Sta=69,81.2
XS Rating Curve= 0 ,0
Exp/Cntr(USF)=0,0
Exp/Cntr=0.3,0.1

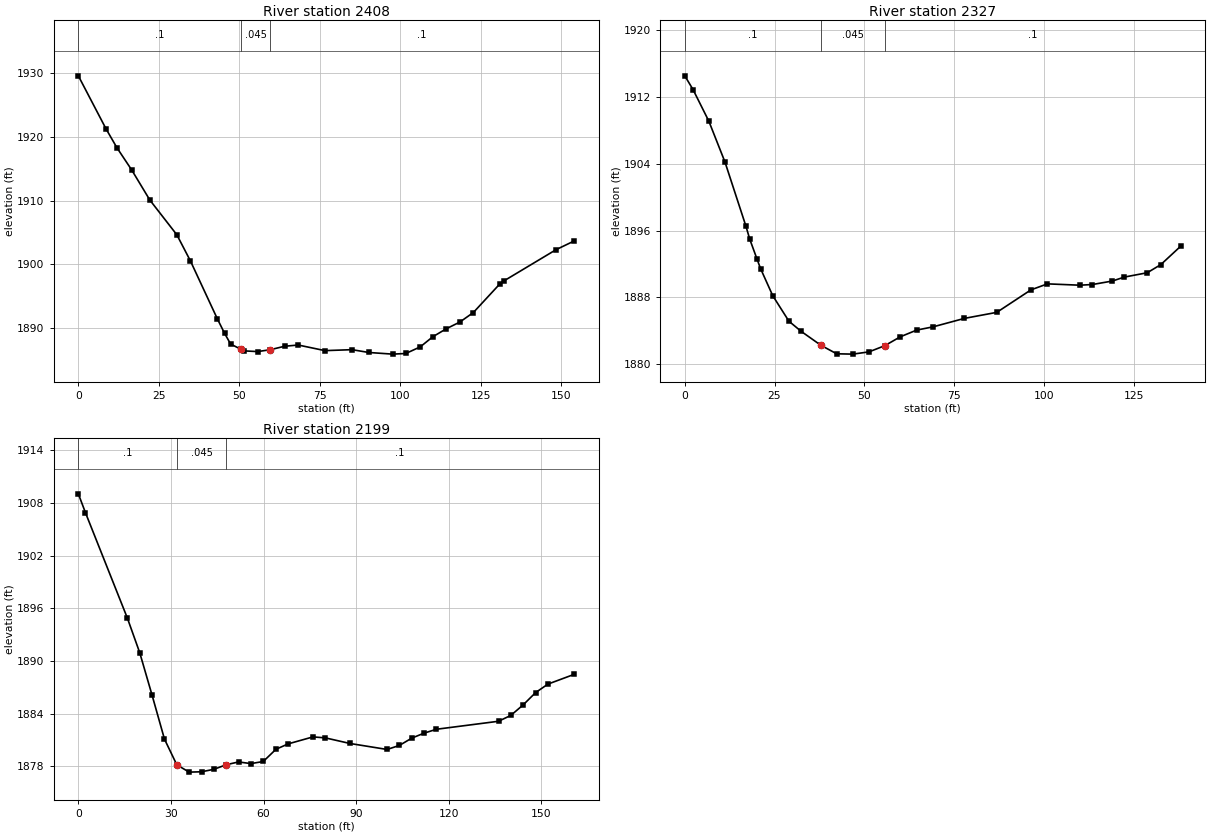
Type RM Length L Ch R = 1 ,2408    ,70.1,81,91.5
XS GIS Cut Line= 3
2160746.93074998624505.6461692992160864.82908784624541.926911664
2160890.73368152624558.374272728
#Sta/Elev= 30
       0  1929.6     8.6 1921.27      12 1918.29    16.6 1914.79    22.2 1910.09
    30.6 1904.62    34.8 1900.53    43.2 1891.39    45.4 1889.16    47.3 1887.45
    50.51886.636    51.5 1886.38    55.7 1886.27    59.61886.562    64.1 1887.11
    68.3  1887.3    76.6 1886.42      85 1886.57    90.2 1886.13    97.6 1885.87
   101.7 1885.97   106.2 1887.01   110.1  1888.6   114.3 1889.86   118.5 1890.91
   122.7 1892.41     131 1896.95   132.1 1897.35   148.4 1902.29     154 1903.65
#Mann= 3 ,-1,0
       0      .1       0    50.5    .045       0    59.6      .1       0
Bank Sta=50.5,59.6
XS Rating Curve= 0 ,0
Exp/Cntr(USF)=0,0
Exp/Cntr=0.3,0.1

Type RM Length L Ch R = 1 ,2327    ,138.7,128,111.8
XS GIS Cut Line= 3
2160749.92023025624539.1580086232160788.57578633624618.036237915
2160832.97743858624641.542994989
#Sta/Elev= 30
       0 1914.53     2.3 1912.88     6.7  1909.1    11.2  1904.2      17 1896.57
    18.1 1894.97    20.1 1892.61    21.1 1891.46    24.5 1888.21      29 1885.16
    32.4 1883.95    37.9 1882.28    42.3 1881.26    46.8 1881.22    51.3 1881.49
    55.7 1882.23      60 1883.29    64.6  1884.1    69.1 1884.48    77.9  1885.5
    86.9 1886.22    96.4 1888.91     101 1889.63     110 1889.47   113.5 1889.55
   119.1 1889.97   122.4 1890.44   128.8 1890.96   132.6 1891.94   138.1 1894.13
#Mann= 3 ,-1,0
       0      .1       0    37.9    .045       0    55.7      .1       0
Bank Sta=37.9,55.7
XS Rating Curve= 0 ,0
Exp/Cntr(USF)=0,0
Exp/Cntr=0.3,0.1

Type RM Length L Ch R = 1 ,2199    ,110.3,119.8,122.7
XS GIS Cut Line= 3
 2160644.3324348624645.0443230512160717.20338172624649.275539324
2160804.64851804624653.976890739
#Sta/Elev= 30
       0 1909.03     2.3 1906.89    15.9 1894.87    19.9 1890.93    23.9 1886.09
    27.9 1881.11    31.9 1878.18    35.9 1877.35    39.9 1877.39    43.9 1877.67
    47.9 1878.19    51.9 1878.51    55.9 1878.32    59.9 1878.56      64 1879.95
      68 1880.57      76 1881.36      80 1881.25      88 1880.61     100 1879.93
     104 1880.39     108 1881.22     112 1881.79     116 1882.23   136.1 1883.14
   140.1 1883.81   144.1 1885.01   148.1  1886.4   152.1 1887.37   160.6 1888.48
#Mann= 3 ,-1,0
       0      .1       0    31.9    .045       0    47.9      .1       0
Bank Sta=31.9,47.9
XS Rating Curve= 0 ,0
Exp/Cntr(USF)=0,0
Exp/Cntr=0.3,0.1