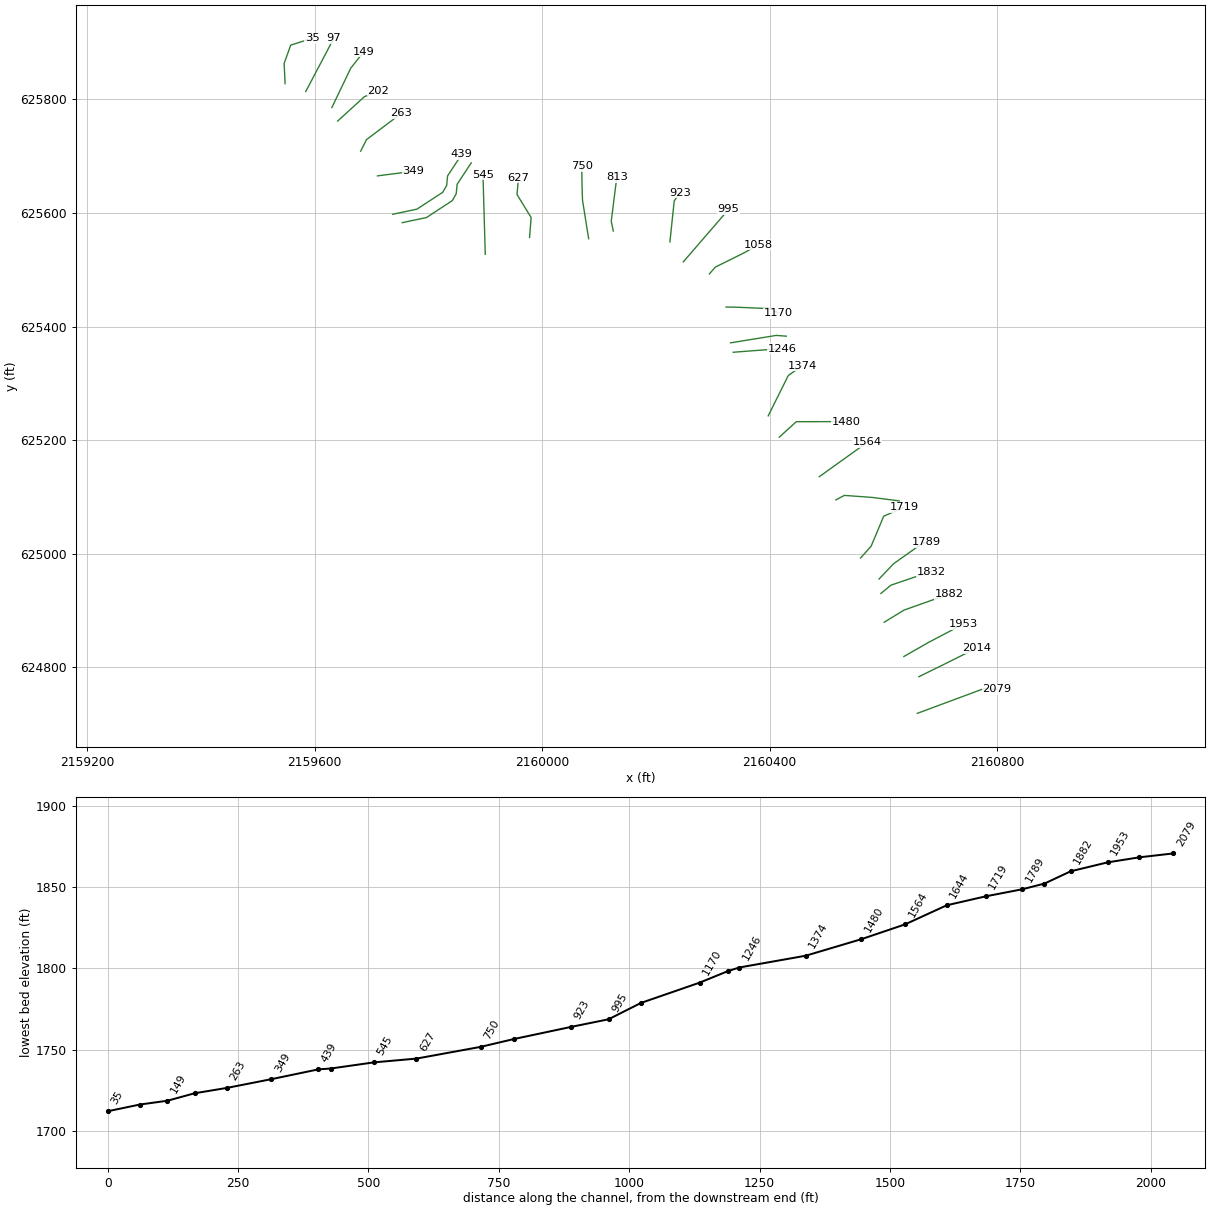
HEC-RAS study HOWELLFK.prj: HOWELLFK

--- HOWELLFK.g01 (geometry) --- (continued)

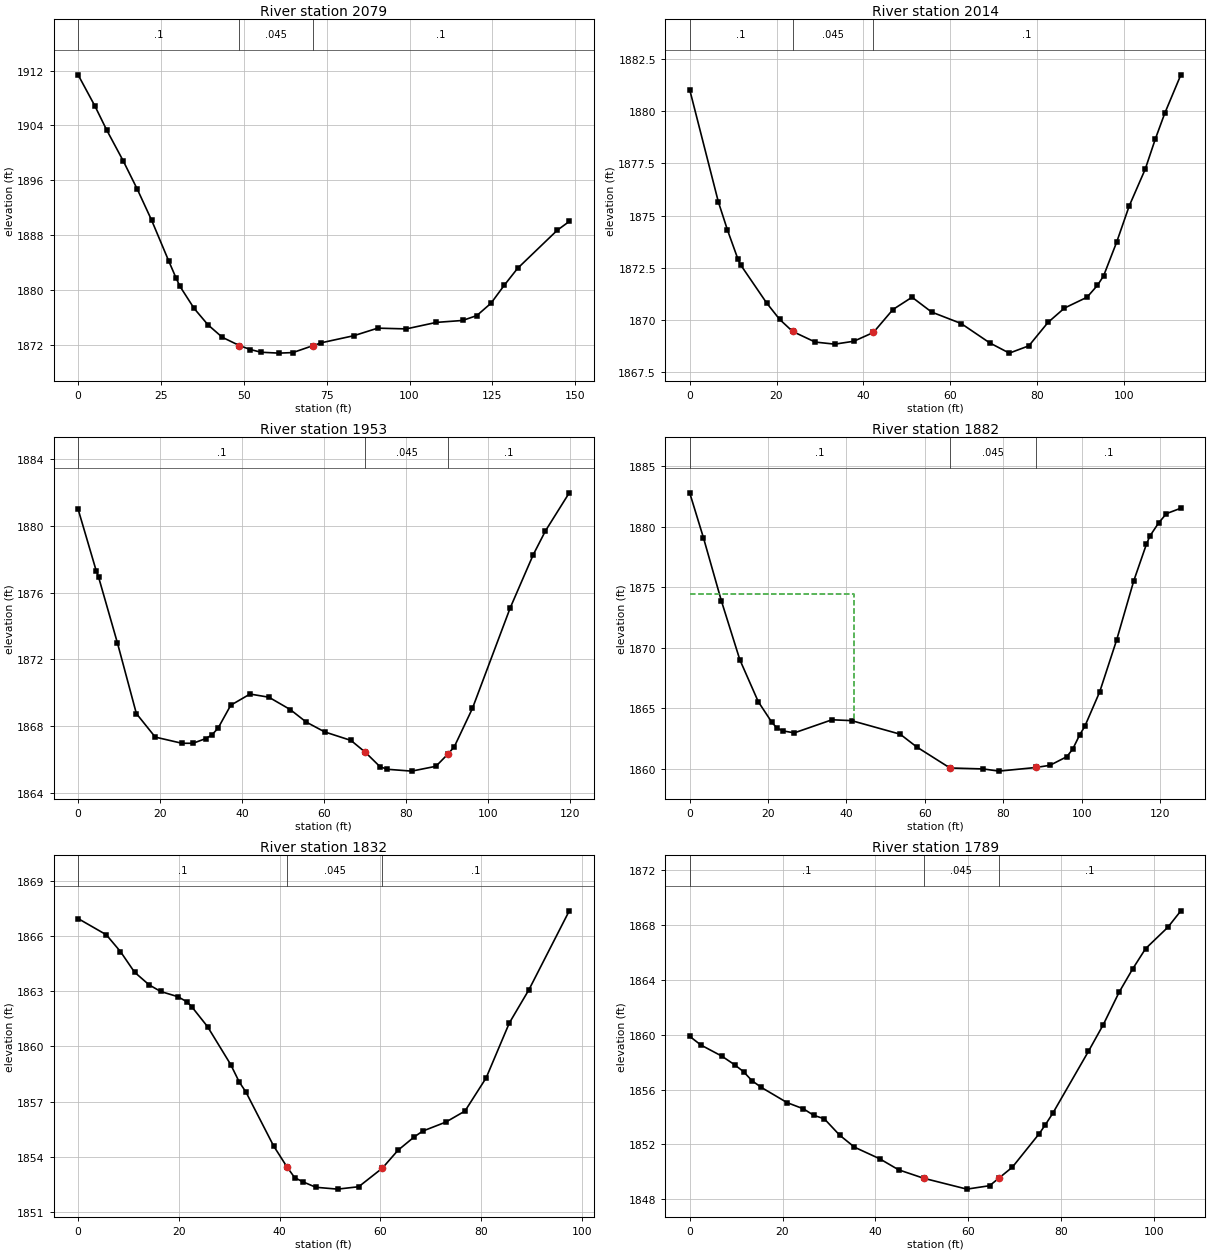
Type RM Length L Ch R = 1 ,2079    ,62.2,65.1,66.7
XS GIS Cut Line= 3
2160659.41514296624718.8943371832160776.60751393624762.498433137
 2160799.7180934624761.182029558
#Sta/Elev= 30
       0 1911.37     5.1  1906.8     8.6 1903.35    13.6 1898.84    17.9 1894.66
    22.2 1890.16    27.3 1884.29    29.5 1881.82    30.7 1880.57      35 1877.33
    39.2 1874.93    43.5 1873.12   48.671871.913      52 1871.33    55.2 1870.94
    60.6 1870.81    64.8 1870.89    70.8 1871.89    73.4 1872.32    83.2 1873.35
    90.4 1874.45      99 1874.34   108.1 1875.29     116 1875.57   120.3 1876.28
   124.6 1878.09   128.6 1880.71   132.6 1883.16   144.6 1888.73   148.2    1890
#Mann= 3 ,-1,0
       0      .1       0   48.67    .045       0    70.8      .1       0
Bank Sta=48.67,70.8
XS Rating Curve= 0 ,0
Exp/Cntr(USF)=0,0
Exp/Cntr=0.3,0.1

Type RM Length L Ch R = 1 ,2014    ,60.6,61.1,62
XS GIS Cut Line= 3
2160662.22961825624783.4256331062160708.01781447 624805.99727913
2160763.47957328624833.728158531
#Sta/Elev= 30
       0 1881.04     6.6 1875.66     8.7 1874.31    11.1 1872.92    11.7 1872.65
    17.7 1870.82    20.7 1870.03    23.7 1869.45    28.9 1868.94    33.4 1868.84
    37.8 1868.98    42.3  1869.4    46.8  1870.5    51.2 1871.09    55.7 1870.38
    62.5 1869.83    69.1  1868.9    73.6 1868.41    78.1 1868.76    82.5 1869.88
    86.3 1870.57    91.5 1871.09    93.9 1871.66    95.3 1872.11    98.3 1873.72
   101.2 1875.46   104.9 1877.23   107.2 1878.66   109.4 1879.91   113.1 1881.75
#Mann= 3 ,-1,0
       0      .1       0    23.7    .045       0    42.3      .1       0
Bank Sta=23.7,42.3
XS Rating Curve= 0 ,0
Exp/Cntr(USF)=0,0
Exp/Cntr=0.3,0.1

Type RM Length L Ch R = 1 ,1953    ,70.6,70.8,65.3
XS GIS Cut Line= 3
2160635.87298458624818.9728406892160678.86659606624843.654358387
 2160740.9684793624876.297655989
#Sta/Elev= 30
       0    1881     4.4 1877.32       5 1876.92     9.6 1872.97    14.2 1868.75
    18.8 1867.34    25.3 1866.97      28 1866.97    31.1 1867.25    32.6 1867.47
    34.1 1867.87    37.2 1869.25    41.9 1869.92    46.5 1869.73    51.7 1868.99
    55.6 1868.24    60.1 1867.65    66.5 1867.14      70 1866.43    73.6 1865.56
    75.4 1865.41    81.3  1865.3    87.2 1865.59    90.2 1866.34    91.7 1866.77
    96.1 1869.06   105.3 1875.08   110.9 1878.26   113.9  1879.7   119.7 1881.98
#Mann= 3 ,-1,0
       0      .1       0      70    .045       0    90.2      .1       0
Bank Sta=70,90.2
XS Rating Curve= 0 ,0
Exp/Cntr(USF)=0,0
Exp/Cntr=0.3,0.1

Type RM Length L Ch R = 1 ,1882    ,50.8,50.3,51.4
XS GIS Cut Line= 3
2160601.23733118624879.359995393 2160636.2362806624900.777262949
2160715.63688227624928.985371437
#Sta/Elev= 30
       0 1882.79     3.5 1879.09     8.1 1873.85    12.8    1869    17.5 1865.54
    20.9 1863.87    22.2 1863.38    23.8 1863.13    26.7 1862.97    36.3 1864.05
    41.3 1863.98    53.7 1862.86    57.9 1861.81    66.4 1860.07    74.9 1859.99
    78.9 1859.81    88.3 1860.11    91.9 1860.29    96.2    1861    97.7 1861.62
    99.5 1862.81   100.8 1863.51   104.6 1866.36   108.9 1870.62   113.3 1875.54
   116.5 1878.53   117.4 1879.22   119.6 1880.29   121.6 1881.07   125.3 1881.52
#Mann= 3 ,-1,0
       0      .1       0    66.4    .045       0    88.3      .1       0
#XS Ineff= 2 , 0
           41.88 1874.45
Permanent Ineff=
       F       F
Bank Sta=66.4,88.3
XS Rating Curve= 0 ,0
Exp/Cntr(USF)=0,0
Exp/Cntr=0.3,0.1

Type RM Length L Ch R = 1 ,1832    ,37.8,42.7,46.4
XS GIS Cut Line= 3
2160595.49123501624930.0301161962160613.25189591 624944.65654282
2160683.77216713624968.685672273
#Sta/Elev= 30
       0 1866.94     5.6 1866.06     8.4 1865.15    11.2 1864.03    14.1 1863.34
    16.4 1862.98    19.8  1862.7    21.6 1862.42    22.6 1862.14    25.7 1861.07
    30.3 1859.01      32 1858.06    33.3 1857.53    38.8  1854.6    41.5 1853.44
      43 1852.87    44.6 1852.65    47.2 1852.35    51.5 1852.25    55.7 1852.38
    60.4 1853.39    63.5 1854.36    66.7 1855.08    68.4  1855.4      73 1855.89
    76.8 1856.49      81 1858.29    85.6 1861.27    89.5 1863.08    97.5 1867.36
#Mann= 3 ,-1,0
       0      .1       0    41.5    .045       0    60.4      .1       0
Bank Sta=41.5,60.4
XS Rating Curve= 0 ,0
Exp/Cntr(USF)=0,0
Exp/Cntr=0.3,0.1

Type RM Length L Ch R = 1 ,1789    ,66.3,69.9,77.2
XS GIS Cut Line= 4
2160592.19712819624955.4430383822160617.99329507624982.529013611
2160664.42639547625015.4191263892160674.74486222625020.578359766
#Sta/Elev= 30
       0 1859.89     2.4 1859.26     6.9 1858.45     9.7 1857.81    11.6 1857.31
    13.4 1856.66    15.4 1856.17      21 1855.05    24.5  1854.6    26.7 1854.13
      29 1853.87    32.3 1852.68    35.5  1851.8    40.9 1850.96      45 1850.15
    50.41849.534    59.7 1848.74    64.6 1848.99   66.661849.557    69.5 1850.34
    75.3 1852.79    76.6 1853.43    78.2 1854.27    85.9  1858.8    89.1 1860.75
    92.5 1863.11    95.4  1864.8    98.2 1866.29     103 1867.85   105.8 1869.05
#Mann= 3 ,-1,0
       0      .1       0    50.4    .045       0   66.66      .1       0
Bank Sta=50.4,66.66
XS Rating Curve= 0 ,0
Exp/Cntr(USF)=0,0
Exp/Cntr=0.3,0.1

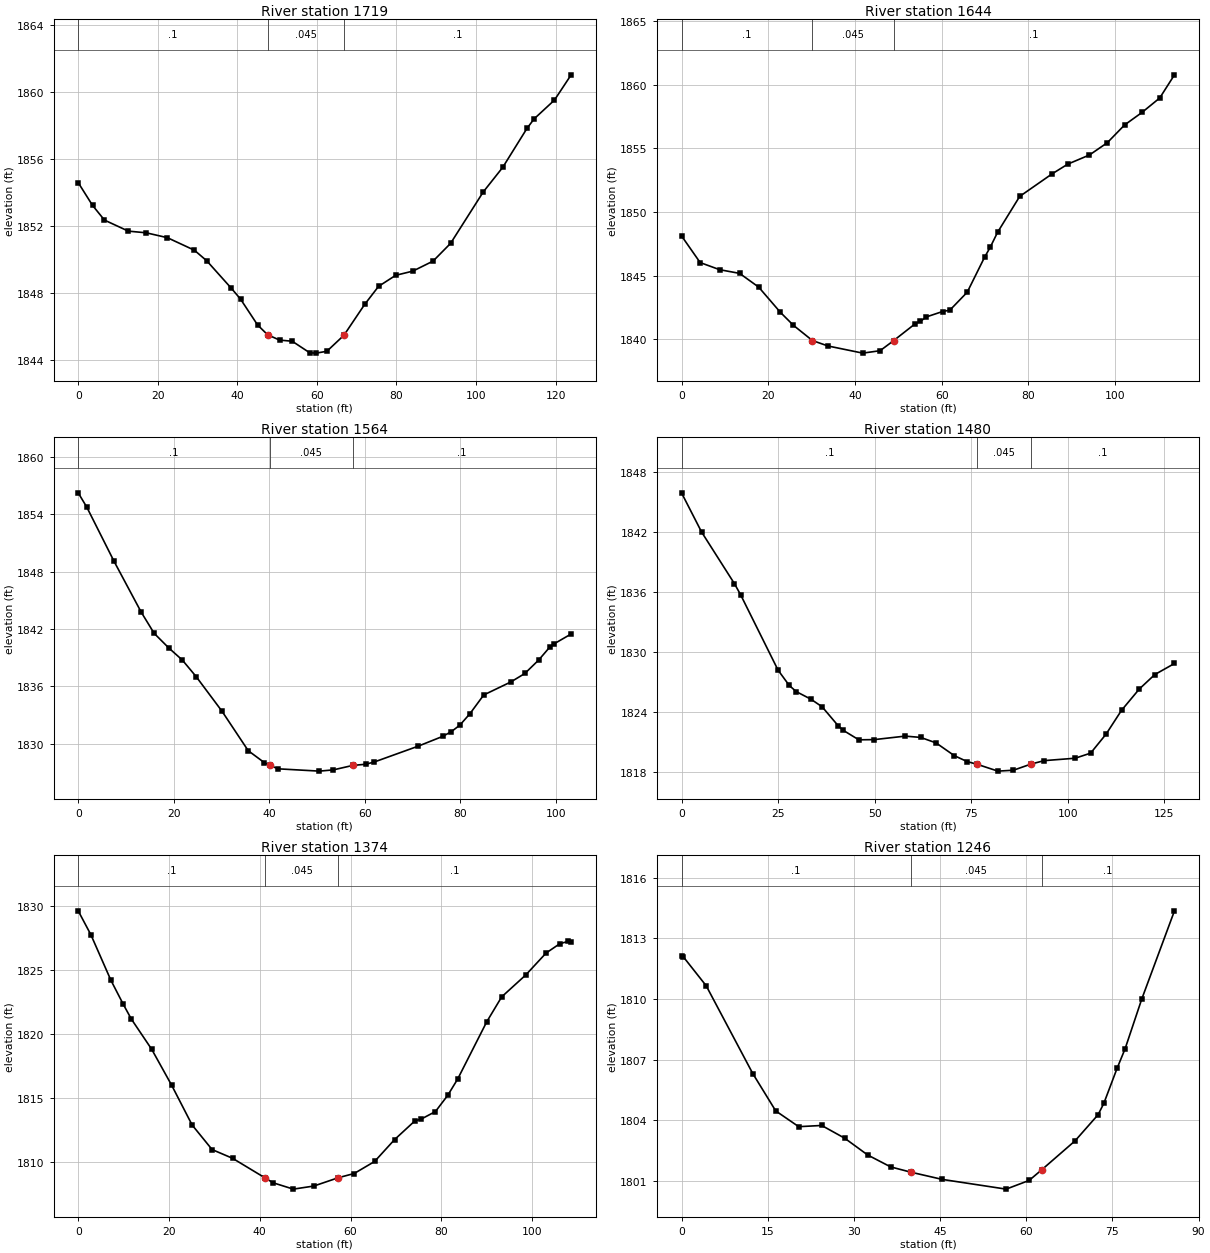
Type RM Length L Ch R = 1 ,1719    ,89.4,74.8,53.3
XS GIS Cut Line= 4
2160559.78807664624992.4499182192160578.29135784 625013.17359316
2160600.49529527625066.0929773832160636.02159517625081.635733588
#Sta/Elev= 30
       0 1854.59     3.6 1853.23     6.6 1852.35    12.6 1851.69    17.1 1851.59
    22.4  1851.3    29.2 1850.55    32.3 1849.92    38.4  1848.3    40.8 1847.63
    45.1 1846.08    47.6  1845.5    50.6 1845.18    53.8 1845.11    58.2 1844.42
    59.8  1844.4    62.5 1844.51    66.8 1845.47      72 1847.31    75.5 1848.39
    79.8 1849.05    84.1  1849.3    89.2  1849.9    93.6 1850.96   101.8 1854.03
   106.7  1855.5   112.8 1857.83   114.6  1858.4   119.7 1859.52   123.9 1861.03
#Mann= 3 ,-1,0
       0      .1       0    47.6    .045       0    66.8      .1       0
Bank Sta=47.6,66.8
XS Rating Curve= 0 ,0
Exp/Cntr(USF)=0,0
Exp/Cntr=0.3,0.1

Type RM Length L Ch R = 1 ,1644    ,65.4,80.2,85.3
XS GIS Cut Line= 4
2160516.37765248625094.7585525892160531.27410692625102.663682544
2160579.92792027625099.1400612422160627.63513309625093.015940784
#Sta/Elev= 30
       0 1848.12     4.3 1846.02     8.8 1845.46    13.4 1845.17    17.8 1844.09
    22.8 1842.11    25.8 1841.09    30.21839.888    33.8 1839.46    41.8  1838.9
    45.8 1839.09    48.91839.876    53.9 1841.21    55.1  1841.4    56.5 1841.75
    60.2 1842.17    61.9 1842.28    65.9 1843.69    69.9 1846.44    71.2 1847.22
    72.9  1848.4      78 1851.22    85.5    1853    89.1 1853.76    94.1 1854.48
    98.2 1855.44   102.2 1856.84   106.2 1857.82   110.3 1858.96   113.7 1860.78
#Mann= 3 ,-1,0
       0      .1       0    30.2    .045       0    48.9      .1       0
Bank Sta=30.2,48.9
XS Rating Curve= 0 ,0
Exp/Cntr(USF)=0,0
Exp/Cntr=0.3,0.1

Type RM Length L Ch R = 1 ,1564    ,89.4,83.4,73.7
XS GIS Cut Line= 2
 2160487.2427825625135.6328475412160571.08032487625195.823903606
#Sta/Elev= 30
       0 1856.27     1.8 1854.77     7.5  1849.1    13.2 1843.76    15.9 1841.55
      19    1840    21.8 1838.75    24.7 1837.01    30.1 1833.39    35.6 1829.25
      39 1827.99    40.11827.704    41.9 1827.35    50.5 1827.11    53.4 1827.24
    57.5 1827.71    60.2 1827.83      62 1828.07    71.2 1829.73    76.3 1830.75
    78.1 1831.24    79.9 1831.93      82 1833.12    84.9 1835.09    90.6 1836.46
    93.5 1837.34    96.4 1838.75    98.7 1840.09    99.6 1840.44   103.2 1841.48
#Mann= 3 ,-1,0
       0      .1       0    40.1    .045       0    57.5      .1       0
Bank Sta=40.1,57.5
XS Rating Curve= 0 ,0
Exp/Cntr(USF)=0,0
Exp/Cntr=0.3,0.1

Type RM Length L Ch R = 1 ,1480    ,91.3,106.8,116.7
XS GIS Cut Line= 3
2160416.83437691625205.159395245 2160446.7714161625232.467434593
2160533.82148616625232.583072151
#Sta/Elev= 30
       0 1845.87     5.2 1841.95    13.7 1836.79    15.3 1835.68      25 1828.14
    27.9 1826.61    29.7    1826    33.5 1825.24    36.4 1824.48    40.5 1822.61
    41.9 1822.12    45.9 1821.18    49.9  1821.2    57.9 1821.55    61.9 1821.42
    65.9 1820.87    70.6  1819.6    73.9 1819.01    76.61818.724    81.9 1818.05
    85.9 1818.14    90.5 1818.76    93.9  1819.1   101.9 1819.34   105.9 1819.85
   109.9 1821.75   113.9 1824.13   118.5 1826.26   122.5  1827.7   127.6 1828.81
#Mann= 3 ,-1,0
       0      .1       0    76.6    .045       0    90.5      .1       0
Bank Sta=76.6,90.5
XS Rating Curve= 0 ,0
Exp/Cntr(USF)=0,0
Exp/Cntr=0.3,0.1

Type RM Length L Ch R = 1 ,1374    ,134.9,127.8,113
XS GIS Cut Line= 3
 2160397.4088981625242.7139837772160432.66903371 625313.70439014
2160456.64592592625330.629255233
#Sta/Elev= 30
       0  1829.6     2.8 1827.73     7.2 1824.18     9.9 1822.32    11.7 1821.15
    16.2 1818.78    20.6 1815.97    25.1 1812.87    29.5 1810.95      34 1810.27
    41.2 1808.73    42.9 1808.36    47.4 1807.86    51.9  1808.1    57.31808.751
    60.8 1809.08    65.3 1810.02    69.7 1811.73    74.2  1813.2    75.5 1813.32
    78.7 1813.92    81.4 1815.18    83.6 1816.46      90 1820.93    93.3 1822.88
    98.6 1824.59   103.1 1826.31   106.1 1827.03     108 1827.22   108.6 1827.14
#Mann= 3 ,-1,0
       0      .1       0    41.2    .045       0    57.3      .1       0
Bank Sta=41.2,57.3
XS Rating Curve= 0 ,0
Exp/Cntr(USF)=0,0
Exp/Cntr=0.3,0.1

Type RM Length L Ch R = 1 ,1246    ,24.4,22.2,23.1
XS GIS Cut Line= 2
2160335.84929962625354.7059751872160421.38579031625361.188039429
#Sta/Elev= 22
       0 1812.11      .3 1812.09     4.3 1810.65    12.4 1806.31    16.4 1804.46
    20.4 1803.68    24.4 1803.74    28.4 1803.11    32.4 1802.28    36.4 1801.69
    39.9 1801.43    45.4 1801.07    56.5 1800.59    60.5 1801.02    62.71801.548
    68.5 1802.98    72.5 1804.27    73.5 1804.83    75.8 1806.56    77.2 1807.53
    80.1 1809.99    85.8 1814.36
#Mann= 3 ,-1,0
       0      .1       0    39.9    .045       0    62.7      .1       0
Bank Sta=39.9,62.7
XS Rating Curve= 0 ,0
Exp/Cntr(USF)=0,0
Exp/Cntr=0.3,0.1

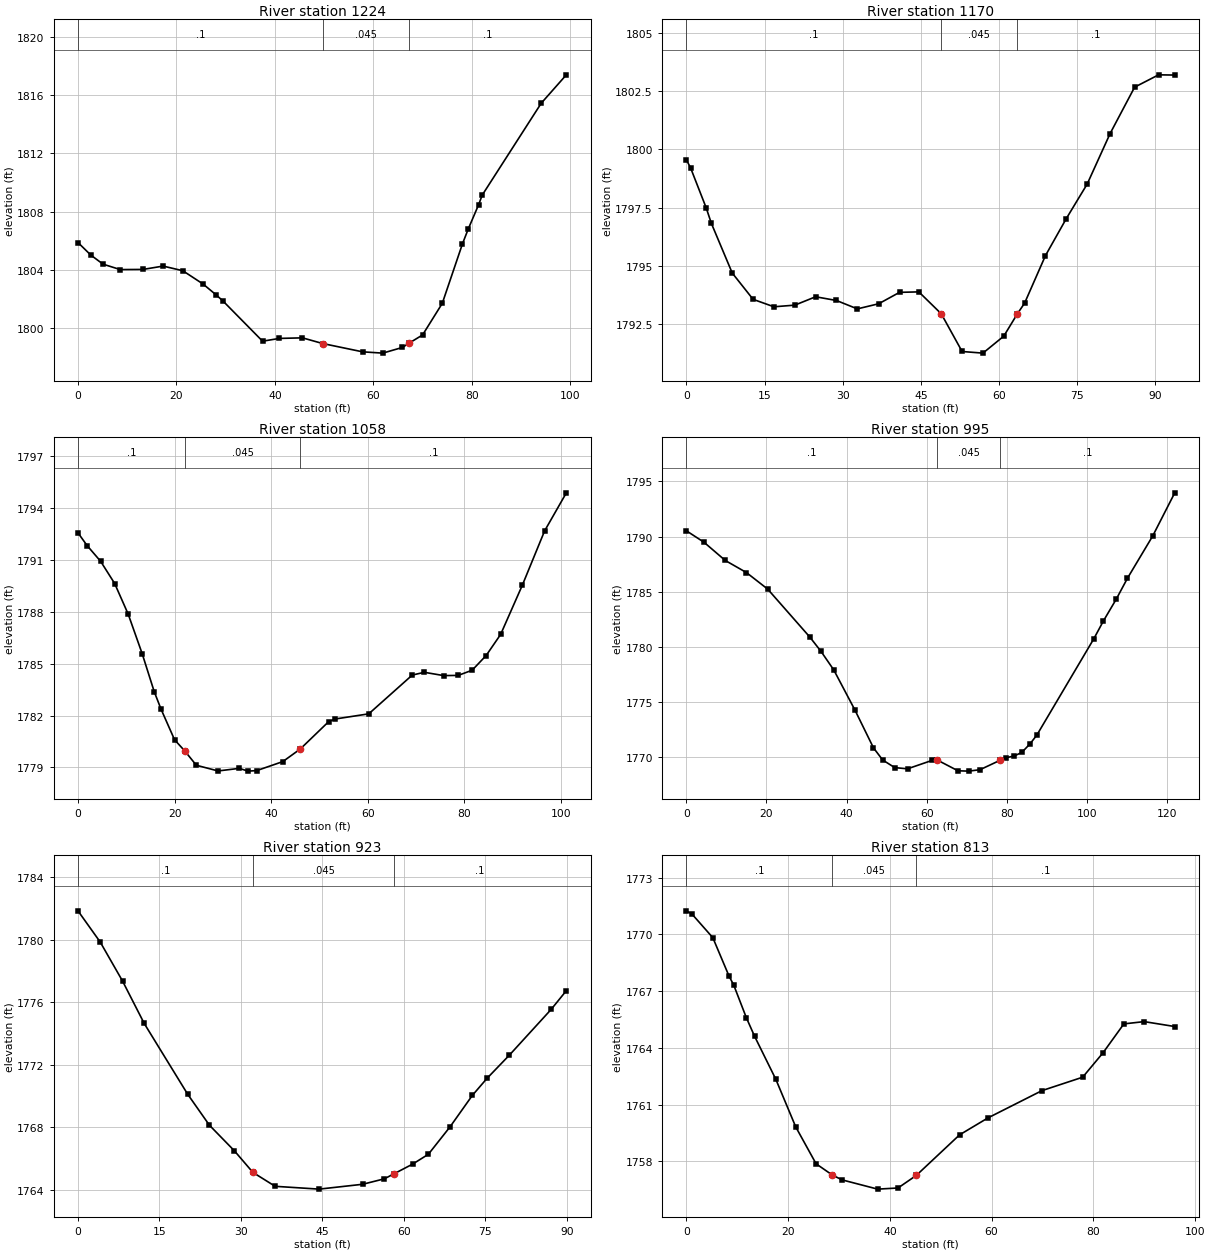
Type RM Length L Ch R = 1 ,1224    ,55.6,53.8,50.7
XS GIS Cut Line= 3
2160331.12237747625371.2400684572160411.44653036625384.330013868
2160429.25186779625382.981124668
#Sta/Elev= 26
       0 1805.88     2.6 1805.02     5.1 1804.39     8.6 1804.02    13.2 1804.03
    17.3 1804.26    21.3 1803.94    25.4 1803.03      28  1802.3    29.4 1801.88
    37.5  1799.1    40.9 1799.29    45.6 1799.33    49.7 1798.94    57.8 1798.37
    61.9 1798.28    65.9 1798.67    67.21798.952      70 1799.53      74  1801.7
    78.1 1805.79    79.3 1806.83    81.4 1808.49    82.1 1809.13    94.1 1815.45
    99.2  1817.4
#Mann= 3 ,-1,0
       0      .1       0    49.7    .045       0    67.2      .1       0
Bank Sta=49.7,67.2
XS Rating Curve= 0 ,0
Exp/Cntr(USF)=0,0
Exp/Cntr=0.3,0.1

Type RM Length L Ch R = 1 ,1170    ,99.9,112.3,112.9
XS GIS Cut Line= 4
2160323.34506216625434.3104815782160343.19273688  625433.9691364
2160401.90907702625431.3811108762160414.75542695625423.574384834
#Sta/Elev= 27
       0 1799.55      .8 1799.21     3.8 1797.49     4.8 1796.82     8.8 1794.69
    12.8 1793.56    16.8 1793.24    20.8 1793.31    24.8 1793.67    28.8 1793.51
    32.8 1793.15    36.9 1793.37    40.9 1793.86    44.6 1793.88    48.9 1792.94
    52.9 1791.32    56.9 1791.25    60.9 1791.98    63.51792.936    64.9  1793.4
    68.9 1795.44    72.9 1797.03    76.9 1798.51    81.3 1800.68      86 1802.67
    90.6  1803.2    93.7 1803.19
#Mann= 3 ,-1,0
       0      .1       0    48.9    .045       0    63.5      .1       0
Bank Sta=48.9,63.5
XS Rating Curve= 0 ,0
Exp/Cntr(USF)=0,0
Exp/Cntr=0.3,0.1

Type RM Length L Ch R = 1 ,1058    ,56.4,62.1,66.7
XS GIS Cut Line= 4
2160294.02076281625492.6345129122160304.39988678625504.589165479
2160354.43738815625529.4115510522160380.07646902625543.844328486
#Sta/Elev= 30
       0 1792.56     1.9 1791.82     4.7 1790.91     7.6 1789.63    10.4 1787.86
    13.3 1785.57    15.8 1783.37    17.2 1782.37      20  1780.6    22.1 1779.96
    24.5 1779.13      29  1778.8    33.4 1778.95    35.2 1778.79      37 1778.82
    42.4 1779.34      461780.063    51.9 1781.65    53.2  1781.8    60.2  1782.1
    69.2 1784.34    71.7  1784.5    75.7 1784.31    78.7 1784.32    81.6 1784.62
    84.5 1785.47    87.5 1786.69      92 1789.54    96.6 1792.67   101.1 1794.87
#Mann= 3 ,-1,0
       0      .1       0    22.1    .045       0      46      .1       0
Bank Sta=22.1,46
XS Rating Curve= 0 ,0
Exp/Cntr(USF)=0,0
Exp/Cntr=0.3,0.1

Type RM Length L Ch R = 1 ,995     ,62,72.1,80.8
XS GIS Cut Line= 2
2160248.13566041625513.8375710372160327.79746568625606.159769436
#Sta/Elev= 30
       0 1790.52     4.4 1789.48     9.7 1787.83      15 1786.73    20.3 1785.23
    30.8 1780.89    33.6 1779.59    36.8  1777.9    42.1 1774.25    46.7 1770.84
      49 1769.74      52 1769.05    55.2 1768.94    61.3  1769.7    62.5 1769.76
    67.8 1768.76    70.5 1768.73    73.3 1768.86    78.4 1769.73    79.7 1769.94
    81.8  1770.1    83.7 1770.42    85.8 1771.21    87.5 1772.01   101.7 1780.73
   104.1 1782.35   107.3 1784.32   110.1 1786.22   116.4 1790.05   121.9 1793.96
#Mann= 3 ,-1,0
       0      .1       0    62.5    .045       0    78.4      .1       0
Bank Sta=62.5,78.4
XS Rating Curve= 0 ,0
Exp/Cntr(USF)=0,0
Exp/Cntr=0.3,0.1

Type RM Length L Ch R = 1 ,923     ,109.4,110.1,109
XS GIS Cut Line= 3
2160224.64760654625549.062867939 2160232.1693433625620.966807861
2160242.05915005625635.496550678
#Sta/Elev= 21
       0 1781.84     4.1 1779.84     8.2 1777.35    12.2 1774.63    20.2  1770.1
    24.2 1768.12    28.8 1766.48    32.21765.101    36.3 1764.21    44.4 1764.03
    52.4 1764.34    56.4 1764.69    58.21765.015    61.6 1765.63    64.5 1766.26
    68.5 1768.02    72.6 1770.03    75.3 1771.12    79.4  1772.6    87.1 1775.53
    89.9 1776.73
#Mann= 3 ,-1,0
       0      .1       0    32.2    .045       0    58.2      .1       0
Bank Sta=32.2,58.2
XS Rating Curve= 0 ,0
Exp/Cntr(USF)=0,0
Exp/Cntr=0.3,0.1

Type RM Length L Ch R = 1 ,813     ,58.8,63.3,68.5
XS GIS Cut Line= 3
2160125.13548101625568.1204312012160121.47672509625585.324614983
2160131.26870645625663.083419633
#Sta/Elev= 23
       0 1771.25     1.1 1771.08     5.2 1769.83     8.4 1767.79     9.3 1767.33
    11.8 1765.59    13.4 1764.62    17.6 1762.33    21.5 1759.82    25.5 1757.87
    28.71757.274    30.6 1757.02    37.6 1756.53    41.6 1756.59    45.21757.256
    53.7  1759.4    59.3  1760.3    69.9 1761.74    77.9 1762.45    81.9 1763.74
      86 1765.27      90 1765.39      96 1765.13
#Mann= 3 ,-1,0
       0      .1       0    28.7    .045       0    45.2      .1       0
Bank Sta=28.7,45.2
XS Rating Curve= 0 ,0
Exp/Cntr(USF)=0,0
Exp/Cntr=0.3,0.1

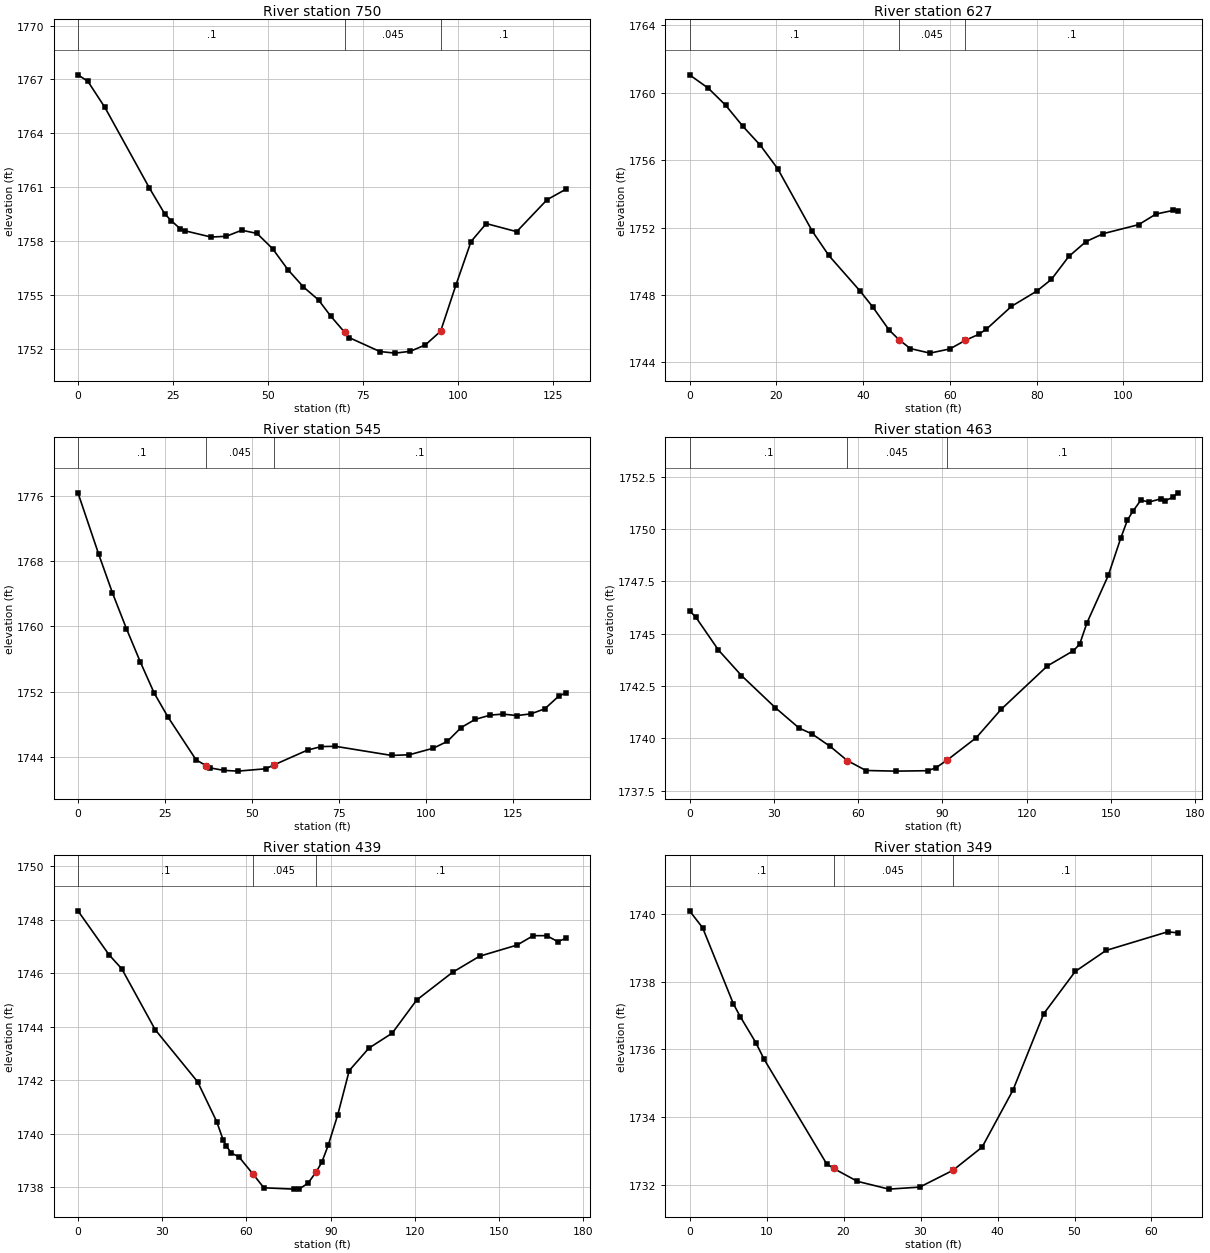
Type RM Length L Ch R = 1 ,750     ,115.9,123,124.2
XS GIS Cut Line= 4
2160081.77364802625554.6531439422160071.02524515625622.009801919
2160070.30868496625641.3569270832160069.59212477625682.200857984
#Sta/Elev= 30
       0 1767.26     2.6  1766.9     7.1 1765.44    18.8 1760.95    22.8 1759.52
    24.6 1759.12    26.9 1758.68    28.1 1758.57      35 1758.22      39 1758.26
    43.1  1758.6    47.1 1758.42    51.2 1757.57    55.2 1756.41    59.3 1755.44
    63.3 1754.71    66.5 1753.81    70.2  1752.9    71.4 1752.61    79.4 1751.84
    83.4 1751.75    87.4 1751.85    91.4 1752.21    95.4 1752.97    99.4 1755.53
   103.4 1757.97   107.4 1758.97   115.4 1758.52   123.4  1760.3   128.4 1760.89
#Mann= 3 ,-1,0
       0      .1       0    70.2    .045       0    95.4      .1       0
Bank Sta=70.2,95.4
XS Rating Curve= 0 ,0
Exp/Cntr(USF)=0,0
Exp/Cntr=0.3,0.1

Type RM Length L Ch R = 1 ,627     ,88.4,81.5,73.2
XS GIS Cut Line= 4
2159977.93072314625556.9263542632159980.67179324625591.901877751
2159955.80499182625632.4475075432159958.52529512625662.137172629
#Sta/Elev= 28
       0 1761.07     4.3 1760.28     8.3 1759.27    12.3 1758.01    16.3 1756.89
    20.3  1755.5    28.3 1751.78    32.1 1750.34    39.3 1748.23    42.2 1747.29
      46 1745.91   48.361745.317    50.9 1744.81    55.4 1744.54      60 1744.79
    63.61745.305    66.6 1745.65    68.4 1745.96    74.2 1747.32      80 1748.22
    83.4 1748.92    87.4 1750.28    91.4 1751.17    95.4 1751.64   103.5 1752.17
   107.5  1752.8   111.5 1753.02   112.5    1753
#Mann= 3 ,-1,0
       0      .1       0   48.36    .045       0    63.6      .1       0
Bank Sta=48.36,63.6
XS Rating Curve= 0 ,0
Exp/Cntr(USF)=0,0
Exp/Cntr=0.3,0.1

Type RM Length L Ch R = 1 ,545     ,104.2,82.9,66.4
XS GIS Cut Line= 2
2159900.01683622625527.2617836352159896.00336224 625667.31555524
#Sta/Elev= 30
       0 1776.43     5.9 1768.95     9.9 1764.13    13.9 1759.75    17.9 1755.64
    21.9  1751.8    25.9 1748.83    33.9 1743.61    36.7 1742.91    37.9 1742.62
    41.9 1742.31    45.9 1742.22    53.9 1742.51    56.2 1742.97    65.9 1744.81
    69.9 1745.24    73.9 1745.27      90 1744.15    95.1 1744.23     102 1745.04
     106 1745.87     110 1747.58     114 1748.58   118.4 1749.11     122 1749.23
     126 1749.05     130 1749.26     134 1749.88     138 1751.44   140.1 1751.85
#Mann= 3 ,-1,0
       0      .1       0    36.7    .045       0    56.2      .1       0
Bank Sta=36.7,56.2
XS Rating Curve= 0 ,0
Exp/Cntr(USF)=0,0
Exp/Cntr=0.3,0.1

Type RM Length L Ch R = 1 ,463     ,22.5,23.5,24.5
XS GIS Cut Line= 6
2159754.05983551 625582.850103772159796.69338594625591.895356977
2159842.11168929625621.6857353852159848.94023982625633.739894029
2159850.60436072625650.5001562792159875.36670153625688.195160279
#Sta/Elev= 30
       0  1746.1     2.2  1745.8    10.3 1744.22    18.5    1743    30.5 1741.47
      39 1740.49    43.6 1740.21    50.1 1739.61   56.141738.938    62.8 1738.46
    73.4 1738.43    84.8 1738.45    87.7 1738.59    91.71738.954   102.1 1740.03
   110.9 1741.38   127.4 1743.46   136.7 1744.19   138.9  1744.5   141.5 1745.52
   149.1 1747.79   153.5 1749.56   155.9 1750.43   157.8 1750.85   160.7 1751.39
   163.6  1751.3     168 1751.46   169.4 1751.37   172.2 1751.53   173.8 1751.74
#Mann= 3 ,-1,0
       0      .1       0   56.14    .045       0    91.7      .1       0
Bank Sta=56.14,91.7
XS Rating Curve= 0 ,0
Exp/Cntr(USF)=0,0
Exp/Cntr=0.3,0.1

Type RM Length L Ch R = 1 ,439     ,92.9,90.5,87.1
XS GIS Cut Line= 6
  2159737.277254625597.5969294892159779.91080443625606.642182697
2159825.32910779625636.4325611052159832.15765831625648.486719749
2159833.82177921625665.2469819982159858.58412002625702.941985999
#Sta/Elev= 30
       0 1748.34    11.1 1746.69    15.6 1746.17    27.5 1743.89    42.6 1741.94
    49.4 1740.45    51.7 1739.76    52.8 1739.54    54.6 1739.27    57.3 1739.13
    62.2  1738.5    66.2 1737.97    76.9 1737.92    78.7 1737.92    81.9 1738.14
   84.781738.559    86.8 1738.92    89.1 1739.56    92.5  1740.7    96.6 1742.36
   103.6  1743.2   111.9 1743.76   120.6    1745   133.4 1746.04     143 1746.64
   156.4 1747.06   162.1 1747.41   166.9 1747.41   170.8 1747.19   173.8 1747.31
#Mann= 3 ,-1,0
       0      .1       0    62.2    .045       0   84.78      .1       0
Bank Sta=62.2,84.78
XS Rating Curve= 0 ,0
Exp/Cntr(USF)=0,0
Exp/Cntr=0.3,0.1

Type RM Length L Ch R = 1 ,349     ,76.8,85.6,90.3
XS GIS Cut Line= 2
 2159710.5350005625665.2278402592159773.38919928625673.342150297
#Sta/Elev= 19
       0 1740.09     1.7 1739.59     5.7 1737.34     6.6 1736.96     8.6  1736.2
     9.7  1735.7    17.8 1732.62    18.71732.482    21.8  1732.1    25.9 1731.87
    29.9 1731.93    34.21732.424      38 1733.11      42 1734.79      46 1737.05
    50.1  1738.3    54.1 1738.92    62.1 1739.47    63.4 1739.44
#Mann= 3 ,-1,0
       0      .1       0    18.7    .045       0    34.2      .1       0
Bank Sta=18.7,34.2
XS Rating Curve= 0 ,0
Exp/Cntr(USF)=0,0
Exp/Cntr=0.3,0.1

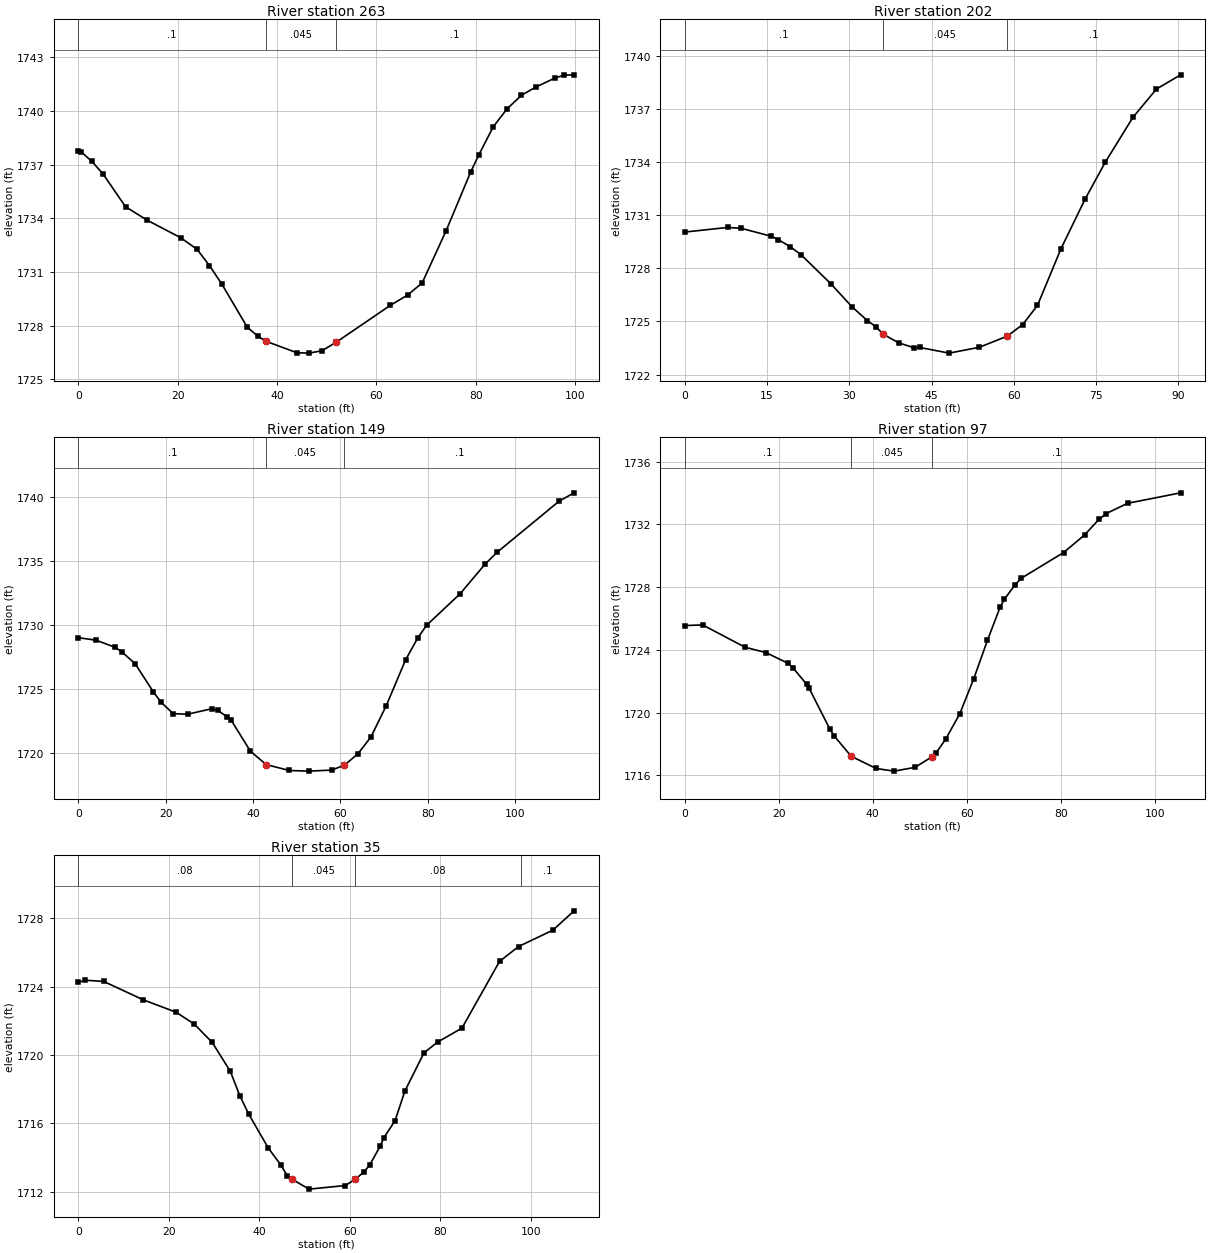
Type RM Length L Ch R = 1 ,263     ,60.2,61.3,63.4
XS GIS Cut Line= 3
2159680.98050057625708.7372159272159691.31397688625729.118732559
 2159752.7207616625775.441786613
#Sta/Elev= 30
       0 1737.76      .5 1737.73     2.7 1737.19       5 1736.47     9.5 1734.65
    13.9 1733.89    20.6 1732.92    23.9 1732.27    26.4 1731.36    28.9 1730.32
      34 1727.92    36.2  1727.4    37.8 1727.13      44 1726.49    46.4 1726.47
      49  1726.6    51.91727.077    62.8 1729.14    66.3 1729.72    69.2 1730.39
      74 1733.29      79 1736.61    80.6 1737.54    83.5 1739.11    86.3 1740.12
    89.2 1740.88    92.1 1741.34      96 1741.85    97.8    1742    99.8 1742.02
#Mann= 3 ,-1,0
       0      .1       0    37.8    .045       0    51.9      .1       0
Bank Sta=37.8,51.9
XS Rating Curve= 0 ,0
Exp/Cntr(USF)=0,0
Exp/Cntr=0.3,0.1

Type RM Length L Ch R = 1 ,202     ,41,52.3,50.6
XS GIS Cut Line= 3
2159640.53829984625761.7396616942159687.48348955625804.562707933
2159712.17706908625815.025846061
#Sta/Elev= 26
       0 1730.04     7.8  1730.3    10.3 1730.25    15.8  1729.8      17 1729.62
    19.2 1729.22    21.2 1728.76    26.6 1727.13    30.5 1725.82    33.3 1725.04
    34.8 1724.71    36.2 1724.27      39 1723.79    41.8 1723.51    42.8 1723.53
    48.2 1723.21    53.7 1723.54    58.8 1724.17    61.6 1724.82    64.3  1725.9
    68.6 1729.11      73 1731.91    76.7    1734    81.7 1736.51      86 1738.11
    90.4 1738.91
#Mann= 3 ,-1,0
       0      .1       0    36.2    .045       0    58.8      .1       0
Bank Sta=36.2,58.8
XS Rating Curve= 0 ,0
Exp/Cntr(USF)=0,0
Exp/Cntr=0.3,0.1

Type RM Length L Ch R = 1 ,149     ,53.4,52.9,51.9
XS GIS Cut Line= 3
2159630.40946882625785.6287792172159663.47263579625854.718346553
2159686.30152295625883.763399293
#Sta/Elev= 30
       0 1729.03     4.1 1728.83     8.4 1728.28      10 1727.91      13    1727
    17.2 1724.78      19 1723.97    21.7  1723.1      25 1723.05    30.5 1723.48
    31.9 1723.35      34 1722.87      35 1722.58    39.4 1720.16      43 1719.12
    48.3 1718.66    52.7 1718.61      58 1718.69    60.91719.075      64 1719.96
      67 1721.29    70.5 1723.73    74.9 1727.29    77.7 1729.01    79.7 1729.99
    87.4 1732.46    93.1 1734.77    95.9 1735.71   110.1  1739.7   113.5 1740.34
#Mann= 3 ,-1,0
       0      .1       0      43    .045       0    60.9      .1       0
Bank Sta=43,60.9
XS Rating Curve= 0 ,0
Exp/Cntr(USF)=0,0
Exp/Cntr=0.3,0.1

Type RM Length L Ch R = 1 ,97      ,61.4,61.4,61.4
XS GIS Cut Line= 2
2159584.51095978625813.835258588 2159633.6577493625907.214158682
#Sta/Elev= 30
       0 1725.55     3.8 1725.59    12.8 1724.17    17.3 1723.82    21.9 1723.15
      23 1722.86    25.9 1721.81    26.4 1721.58    30.9 1718.92    31.8  1718.5
    35.4 1717.21    40.7 1716.43    44.5 1716.26      49  1716.5    52.6 1717.18
    53.5 1717.43    55.5  1718.3    58.5 1719.91    61.5 1722.17    64.4 1724.61
    67.1 1726.73      68 1727.23    70.3 1728.16    71.6 1728.57    80.6 1730.21
    85.1 1731.34    88.1 1732.32    89.7  1732.7    94.2 1733.35   105.5 1734.02
#Mann= 3 ,-1,0
       0      .1       0    35.4    .045       0    52.6      .1       0
Bank Sta=35.4,52.6
XS Rating Curve= 0 ,0
Exp/Cntr(USF)=0,0
Exp/Cntr=0.3,0.1

Type RM Length L Ch R = 1 ,35      ,,,
XS GIS Cut Line= 4
2159548.14233553625827.596359654 2159546.4758193 625863.22597459
2159558.07219786625895.5081340482159595.92094189625907.399098089
#Sta/Elev= 30
       0 1724.24     1.5 1724.37     5.6  1724.3    14.3 1723.23    21.6  1722.5
    25.6 1721.81    29.6 1720.73    33.6 1719.04    35.7 1717.61    37.7 1716.52
      42 1714.55    44.8 1713.55    46.2 1712.92   47.22 1712.73      51 1712.15
      59 1712.36 61.21311712.726    63.2 1713.17    64.4 1713.56    66.7 1714.65
    67.5 1715.14      70 1716.15    72.2  1717.9    76.4 1720.12    79.4 1720.75
    84.8 1721.57    93.1 1725.47    97.3 1726.34   104.9  1727.3   109.6 1728.43
#Mann= 4 ,-1,0
       0     .08       0   47.22    .045       0 61.2131     .08       0
   97.74      .1       0
Bank Sta=47.22,61.2131
XS Rating Curve= 0 ,0
Exp/Cntr(USF)=0,0
Exp/Cntr=0.3,0.1
LCMann Table=0

Chan Stop Cuts=-1
Use User Specified Reach Order=0
Composite Channel Slope=5